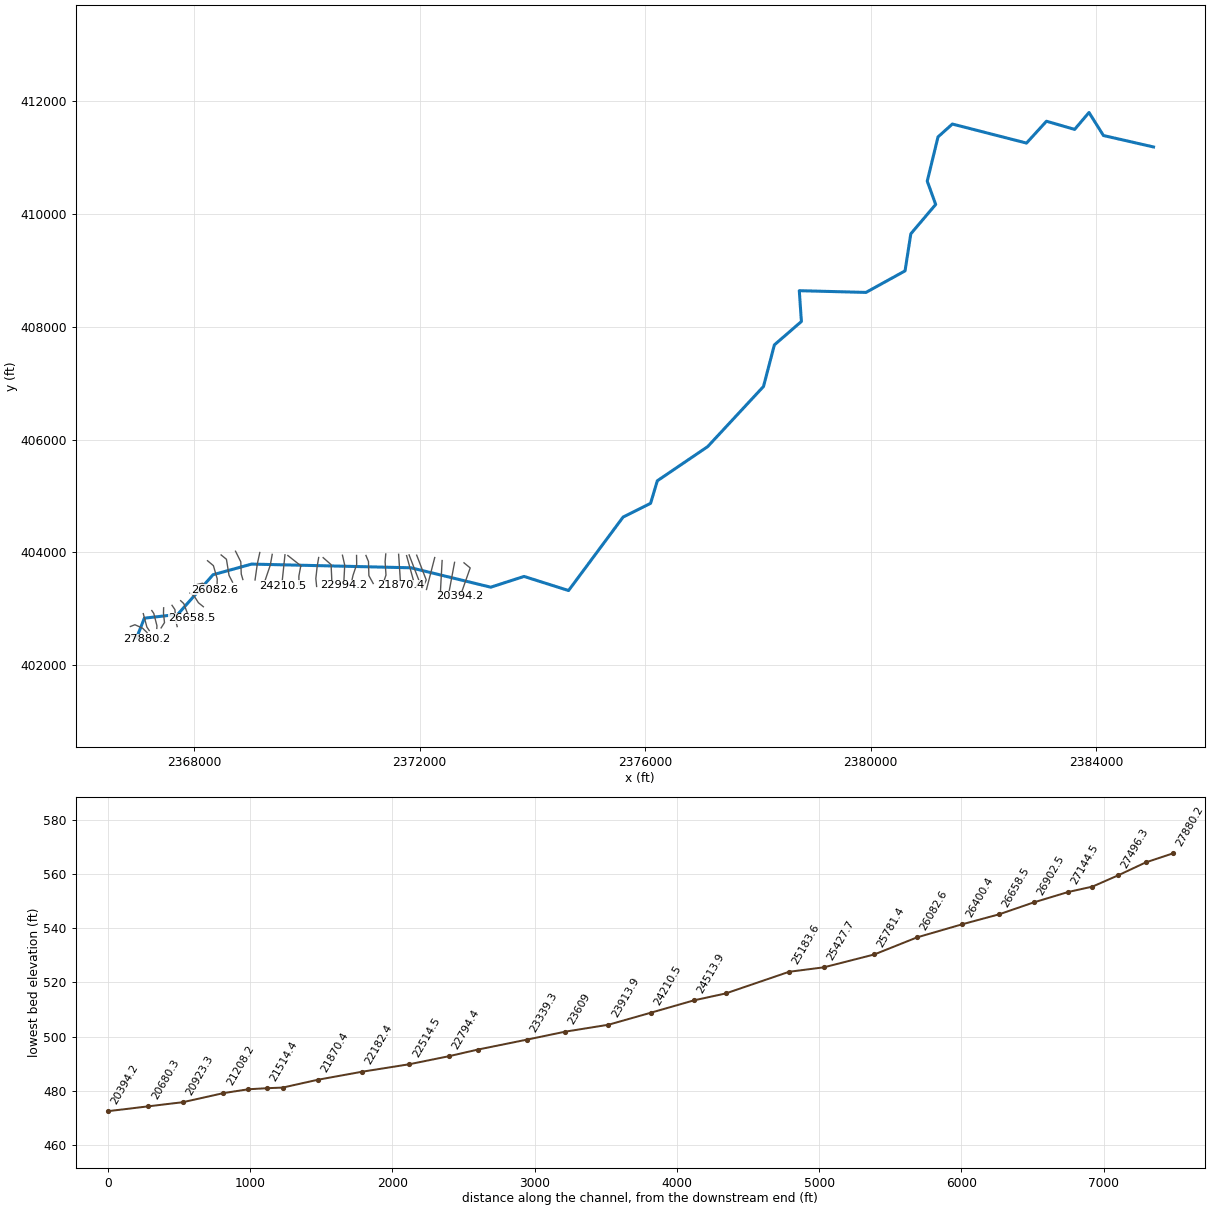
--- CHERRYRUN.prj (project) ---

Proj Title=CHERRYRUN
Current Plan=p01
Default Exp/Contr=0,0
English Units
Geom File=g01
Flow File=f01
Plan File=p01
BEGIN DESCRIPTION:
END DESCRIPTION:
DSS Export Rating Curves= 0
DSS Export Rating Curve Sorted= 0
DSS Export Volume Flow Curves= 0
DXF OffsetX= 0
DXF OffsetY= 0
DXF ScaleX= 0
DXF ScaleY= 0

--- CHERRYRUN.p01 (plan) ---

Plan Title=Floodplain
Program Version=4.00
Geom File=g01
Flow File=f01
K Sum by GR=0
Std Step Tol=0.01
Critical Tol=0.01
Num of Std Step Trials=20
Max Error Tol=0.3
Flow Tol Ratio=0.001
Split Flow NTrial=30
Split Flow Tol=0.02
Split Flow Ratio=0.02
Log Output Level=0
Friction Slope Method=1
Unsteady Friction Slope Method=2
Unsteady Bridges Friction Slope Method=1
Global Log Level=0
CheckData=False
Run HTab=0
Run UNet=0
Run PostProcess=0
UNET Theta=0
UNET Theta Warmup=0
UNET ZTol=0
UNET ZSATol=0
UNET MxIter=0
UNET MaxInSteps=0
UNET DtIC=0
UNET DtMin=0
UNET MaxCRTS=0
UNET WFStab=0
UNET SFStab=0
UNET WFX=0
UNET SFX=0
UNET DSS MLevel=0
UNET DZMax Abort=0
UNET Convert EG Bridges=0
UNET Use Existing IB Tables=0
UNET Froude Limit=0
UNET Froude Power=0
Write IC File=0
Echo Input=False
Echo Output=False
Write Detailed=0

--- CHERRYRUN.f01 (steady flow) ---

Flow Title=NFF Regression Equation
Program Version=4.00
Number of Profiles=1
Profile Names=P100yr
River Rch & RM=CHERRYRUN,Main      ,27880.2
483.8320
River Rch & RM=CHERRYRUN,Main      ,27496.3
668.3336
River Rch & RM=CHERRYRUN,Main      ,26082.6
678.1409
River Rch & RM=CHERRYRUN,Main      ,25781.4
758.7608
River Rch & RM=CHERRYRUN,Main      ,23913.9
817.2598
River Rch & RM=CHERRYRUN,Main      ,23609
911.8194
River Rch & RM=CHERRYRUN,Main      ,21624.8
965.9568
River Rch & RM=CHERRYRUN,Main      ,16330.8
1065.499
River Rch & RM=CHERRYRUN,Main      ,10652.9
1173.768
River Rch & RM=CHERRYRUN,Main      ,8821.5
1302.283
River Rch & RM=CHERRYRUN,Main      ,5149.1
1351.060
River Rch & RM=CHERRYRUN,Main      ,4374.9
1922.126
River Rch & RM=CHERRYRUN,Main      ,506.9
2044.745
Boundary for River Rch & Prof#=CHERRYRUN,Main      ,1
Up Type=0
Dn Type=3
Dn Slope=0.002109

--- CHERRYRUN.g01 (geometry) ---

Geom Title=USGS 10m DEM
Program Version=4.10

River Reach=CHERRYRUN       ,Main
Reach XY= 30
     2366979.549      402482.591     2367118.438      402833.286
     2367708.716      402899.257     2368336.585      403603.273
     2369020.439      403791.641     2371846.813      403726.192
     2373262.535      403381.897     2373852.813      403572.869
     2374642.743      403322.869     2375610.376      404625.172
     2376097.604      404868.007     2376217.147      405268.076
     2377109.834      405873.328     2378100.719      406940.277
     2378293.753      407677.581     2378772.952      408091.966
     2378735.593      408638.193     2379918.785      408607.591
     2380611.493      408989.535     2380714.001      409646.223
     2381154.896      410166.619      2381005.33      410579.749
     2381196.563      411364.536     2381451.305      411592.186
     2382766.301      411254.947     2383120.174      411642.313
      2383619.76      411497.325     2383874.818      411796.794
     2384130.591      411388.841     2385019.144      411186.017

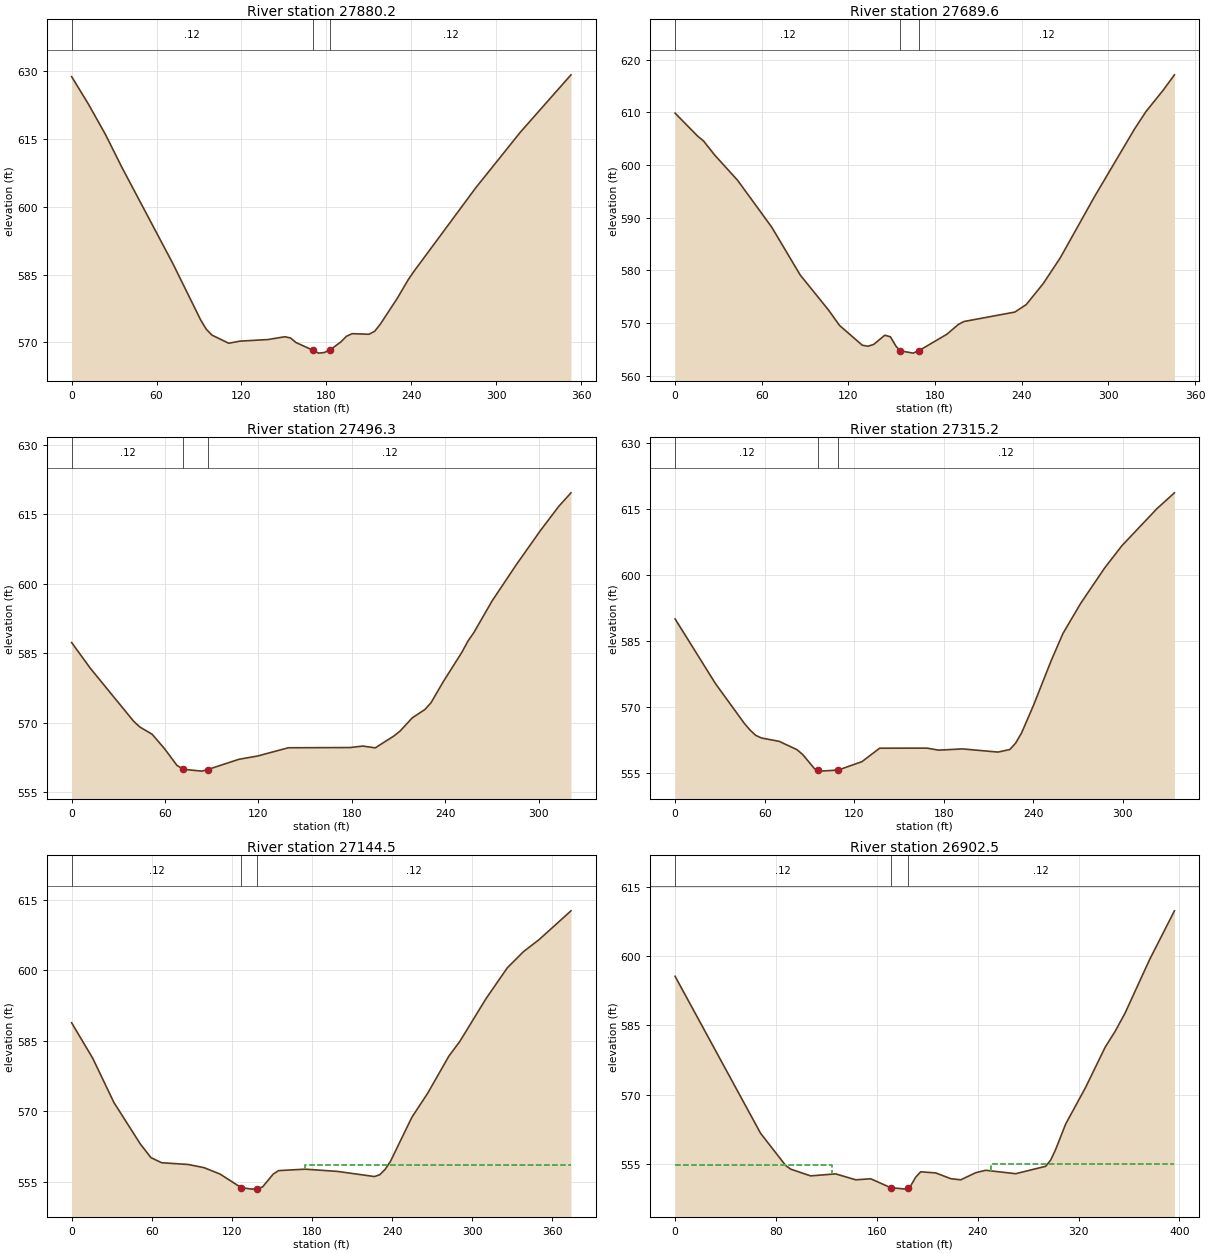
Type RM Length L Ch R = 1 ,27880.2 ,195,190.6,186.1
XS GIS Cut Line= 2
2366809.95174697402539.5431146772367153.70171563402460.116108179
#Sta/Elev= 30
       0  628.75    11.9  622.66    23.8  616.03    35.7  608.59    71.4  587.51
    91.2  574.96    95.1  572.94    99.1  571.63     111  569.82   118.9  570.29
   138.7  570.64   150.6  571.26   154.6     571   158.6  569.97   170.5  568.28
   174.4  567.64   178.4  567.76   182.4  568.31   190.3  570.14   194.2  571.37
   198.2  571.94   210.1  571.81   214.1  572.47     218     574   229.9  579.67
   237.8  583.86   241.8  585.69   285.4  604.13   317.1   616.5   352.8  629.15
#Mann= 3 ,-1 , 0
       0     .12       0   170.5    .045       0   182.4     .12       0
Bank Sta=170.5,182.4
XS Rating Curve= 0 ,0
Exp/Cntr=0.3,0.1

Type RM Length L Ch R = 1 ,27689.6 ,214.1,193.3,141.9
XS GIS Cut Line= 4
2366869.84762456402685.376484424 2366950.5767938402716.626421928
2367085.99351771402655.4283815922367165.42052422402578.605700597
#Sta/Elev= 30
       0  609.85    15.7  605.47    19.7  604.57    27.5  601.87    43.3   597.1
    66.9  588.22    86.6  579.15   106.1  572.54   113.9  569.56   129.6  565.82
   133.5  565.63   137.4  565.96   145.2  567.72   149.1  567.41     153   565.6
  155.99  564.75   164.8  564.32   168.7  564.77   188.2  567.91   196.1  569.76
     200  570.32   235.2  572.11   243.1  573.53   254.9  577.53   266.7  582.42
   290.4  594.03     318  606.81   325.9  610.12   337.8  614.17   345.7  617.12
#Mann= 3 ,-1 , 0
       0     .12       0  155.99    .045       0   168.7     .12       0
Bank Sta=155.99,168.7
XS Rating Curve= 0 ,0
Exp/Cntr=0.3,0.1

Type RM Length L Ch R = 1 ,27496.3 ,181.3,181.1,222.3
XS GIS Cut Line= 3
2367099.01448905402913.241186172 2367162.8165268402674.959838584
2367204.48311013402613.761798263
#Sta/Elev= 30
       0   587.3    11.9   581.8    39.8  570.33    43.8  569.08    51.7  567.52
    59.7  564.39    67.6  560.82    71.6  559.96    83.6  559.56    87.5  559.91
   107.4  562.11   119.4  562.82   139.2   564.6     179  564.65     187  564.97
     195  564.58   206.9  567.12   210.9  568.19   218.8  571.06   226.8  572.83
   230.8  574.31   238.7  578.87   250.6  585.18   254.5   587.6   258.4  589.49
     270  596.26   285.6   604.1   301.2  611.52   312.9   616.7   320.7   619.6
#Mann= 3 ,-1 , 0
       0     .12       0    71.6    .045       0    87.5     .12       0
Bank Sta=71.6,87.5
XS Rating Curve= 0 ,0
Exp/Cntr=0.3,0.1

Type RM Length L Ch R = 1 ,27315.2 ,173.5,170.6,167.2
XS GIS Cut Line= 4
2367250.05618171 402967.928412752367285.21227938402917.147346333
 2367341.2019968402698.397127673 2367338.5976713402651.522221416
#Sta/Elev= 30
       0  589.99      27  575.31    46.3  566.28    50.2  564.73      54  563.52
    57.9  562.92    69.7  562.16    81.6  560.28    85.5  559.16    93.4  555.94
   95.83  555.62    97.4  555.39   109.3  555.64   125.2  557.55     137   560.6
   168.7  560.62   176.6  560.16   192.5  560.44   216.3  559.72   224.2   560.3
   228.1  561.74   232.1  564.08     240  570.27   251.9  580.48   259.8  586.67
   271.7  593.53   287.6   601.5   299.3  606.63   322.8  615.06   334.5  618.65
#Mann= 3 ,-1 , 0
       0     .12       0   95.83    .045       0   109.3     .12       0
Bank Sta=95.83,109.3
XS Rating Curve= 0 ,0
Exp/Cntr=0.3,0.1

Type RM Length L Ch R = 1 ,27144.5 ,241.9,242,241.1
XS GIS Cut Line= 4
2367459.92649688 403016.116308512367457.08726372402921.053506508
2367475.31655797402754.3868450972367415.42068039402660.637032583
#Sta/Elev= 30
       0  588.81    15.8  581.27    31.7  571.83    51.5  562.99    59.4  560.11
    67.4  559.02    87.2  558.65    99.1  557.98   111.1  556.62     127  553.72
     135   553.4     139  553.51     143  553.86     151  556.61     155  557.34
   174.9  557.65   198.9  557.18   226.8  556.08   230.8  556.47   234.8  557.61
   238.8  559.31   254.8  568.68   266.7  573.83   282.6  581.74   290.6  584.78
   310.4  593.97   326.3  600.51   338.3  603.93   350.2  606.54     374  612.65
#Mann= 3 ,-1 , 0
       0     .12       0     127    .045       0     139     .12       0
#XS Ineff= 2 , 0
                          174.61          558.51
Permanent Ineff=
       F       F
Bank Sta=127,139
XS Rating Curve= 0 ,0
Exp/Cntr=0.3,0.1

Type RM Length L Ch R = 1 ,26902.5 ,237.8,244,248.5
XS GIS Cut Line= 4
2367608.58105522403060.6044085032367660.21218555402984.855544254
2367677.13931705402775.2201367622367700.57693422402684.074321672
#Sta/Elev= 30
       0  595.65    67.8  561.66    87.7  554.68    91.7  553.89   107.5  552.43
   127.4  552.86   143.3  551.58   155.2   551.8     171  549.88   182.9  549.56
  184.94  549.91   186.9  550.29   190.9  552.16   194.8  553.31   206.8  553.07
   218.7  551.82   226.6  551.58   238.5  553.12   246.4  553.64   270.2   552.9
     294  554.51     298  555.89     302  558.23   309.8  563.65   325.5  571.52
   341.2  580.32     349   583.7   356.9  587.66   376.5  599.33   396.1  609.83
#Mann= 3 ,-1 , 0
       0     .12       0     171    .045       0  184.94     .12       0
#XS Ineff= 2 , 0
          124.25  554.78  250.98           554.9
Permanent Ineff=
       F       F
Bank Sta=171,184.94
XS Rating Curve= 0 ,0
Exp/Cntr=0.3,0.1

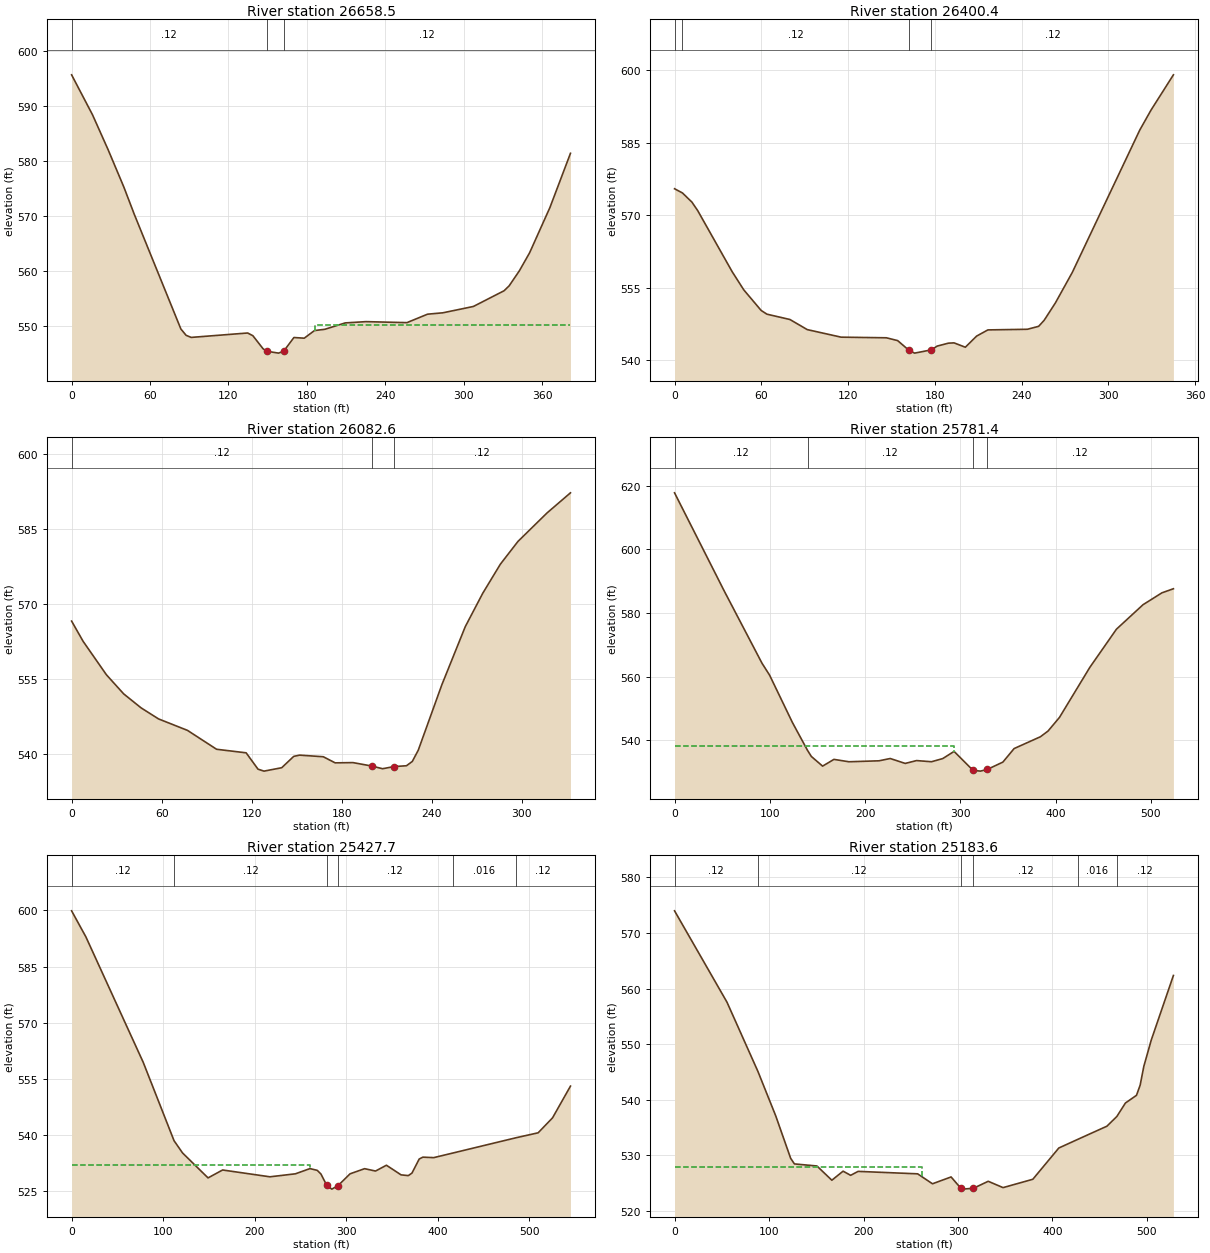
Type RM Length L Ch R = 1 ,26658.5 ,253.1,258.1,262.6
XS GIS Cut Line= 4
2367761.57582797 403143.069466682367817.20006055403091.597128674
2367883.36757913 402914.912114592367963.77850755402829.611104086
#Sta/Elev= 30
       0  595.62      16  588.37    27.9  582.06    39.9  575.31    47.9  570.36
    83.6  549.53    87.6  548.38    91.5     548   134.7   548.8   138.7  548.31
   146.5  545.94  149.43  545.49   158.3  545.15   162.3  545.51   170.1  547.98
     178  547.86   185.8  549.24   193.7  549.47   209.4  550.63   225.2  550.86
   256.6  550.68   272.3  552.21     284  552.46   307.4  553.61   330.9  556.46
   334.8  557.36   342.6  560.08   350.4  563.33     366  571.57   381.7  581.39
#Mann= 3 ,-1 , 0
       0     .12       0  149.43    .045       0   162.3     .12       0
#XS Ineff= 2 , 0
                          186.17          550.24
Permanent Ineff=
       F       F
Bank Sta=149.43,162.3
XS Rating Curve= 0 ,0
Exp/Cntr=0.3,0.1

Type RM Length L Ch R = 1 ,26400.4 ,308.8,317.8,326.4
XS GIS Cut Line= 4
2367927.32024713403278.4320568442368001.85717155403224.807820261
2368077.37801789403106.318227842 2368164.9503493403035.376440585
#Sta/Elev= 30
       0  575.47    5.45574.6046      12  572.71      16  570.96    39.9   558.3
    47.9  554.56    59.9  550.31    63.9  549.54    79.8  548.44    91.8  546.35
   115.2  544.79   146.5  544.66   154.3  544.08   162.1  542.08     166  541.49
   177.7  542.17   181.6  542.94   189.4  543.55   193.3  543.61   201.1  542.71
   208.9  545.01   216.7  546.29     244  546.42   251.8  547.03   255.6  548.27
   263.4  551.88   275.1  558.19   321.7  587.58   329.5  591.72     345  599.02
#Mann= 4 ,-1 , 0
       0     .12       0    5.45     .12       0   162.1    .045       0
   177.7     .12       0
Bank Sta=162.1,177.7
XS Rating Curve= 0 ,0
Exp/Cntr=0.3,0.1

Type RM Length L Ch R = 1 ,26082.6 ,316.2,301.2,282.8
XS GIS Cut Line= 4
2368059.14905173403431.839230344 2368149.4031363403452.626262262
2368271.38845664403371.9433527592368358.62811156403338.089089751
#Sta/Elev= 30
       0  566.58     7.7  562.53    23.2  555.87    34.7  552.06    46.3  549.27
    57.9  547.07    77.2  544.78    96.6  541.01   116.3   540.3   124.2  537.04
   128.2  536.65     140  537.33     148  539.59   151.9  539.84   167.7  539.52
   175.6   538.3   187.5  538.35   199.9  537.67   207.2  537.13   214.9  537.56
   223.1  537.72     227  538.58     231  540.84   246.7  553.88   262.3  565.47
     274  572.16   285.7  577.94   297.4  582.47   316.8  588.16   332.4  592.17
#Mann= 3 ,-1 , 0
       0     .12       0   199.9    .045       0   214.9     .12       0
Bank Sta=199.9,214.9
XS Rating Curve= 0 ,0
Exp/Cntr=0.3,0.1

Type RM Length L Ch R = 1 ,25781.4 ,356.3,353.7,348.1
XS GIS Cut Line= 4
2368238.51811555403851.3124727612368342.54645081403764.116124839
2368410.71134073403529.4955310972368406.92099397    403386.03486
#Sta/Elev= 30
       0  617.71    51.9  587.03    91.8  564.21    99.8  560.45   123.8  545.55
  139.59536.8394   143.6  534.93   155.4   531.9   167.3  534.02     183  533.27
   214.6  533.57   226.4  534.29   242.1  532.75     254  533.64   269.7  533.28
   281.5  534.27   293.4  536.52   313.2   530.6     321  530.33   328.2  530.86
   344.6  533.16   356.4  537.41     384  541.12     392  542.91     404  547.19
   435.9  562.92   463.8  574.89   491.7  582.58   511.6  586.32   523.6  587.59
#Mann= 4 ,-1 , 0
       0     .12       0  139.59     .12       0   313.2    .045       0
   328.2     .12       0
#XS Ineff= 2 , 0
           293.5  538.07
Permanent Ineff=
       F       F
Bank Sta=313.2,328.2
XS Rating Curve= 0 ,0
Exp/Cntr=0.3,0.1

Type RM Length L Ch R = 1 ,25427.7 ,247,244.1,249.5
XS GIS Cut Line= 4
 2368479.8375148403953.7430421712368573.77663139  403877.2012005
2368620.34674822 403590.693243342368681.54478855403472.203650922
#Sta/Elev= 30
       0  599.91    15.6  592.95    78.2  559.46  111.88538.5172   121.2  535.24
     149  528.59   164.9   530.7   216.6  528.88   244.4  529.68   260.3  531.07
   268.3   530.6   272.3  529.62  278.62  526.61   284.2  525.59     291  526.53
   304.1  529.68     320  531.05   331.9  530.42   343.8  531.97   359.8   529.4
   367.7   529.2   371.7  529.87   379.6  533.63   383.6  534.13   395.5     534
  416.11535.2137   485.6 539.323   509.5  540.63   525.2  544.62   544.8   553.1
#Mann= 6 ,-1 , 0
       0     .12       0  111.88     .12       0  278.62    .045       0
     291     .12       0  416.11    .016       0   485.6     .12       0
#XS Ineff= 2 , 0
          260.06  532.03
Permanent Ineff=
       F       F
Bank Sta=278.62,291
XS Rating Curve= 0 ,0
Exp/Cntr=0.3,0.1

Type RM Length L Ch R = 1 ,25183.6 ,451.8,446.5,439.9
XS GIS Cut Line= 4
2368735.04599388404019.7153511792368828.67999297403831.578588337
2368836.72164355403615.538338006 2368865.2540668403517.979149923
#Sta/Elev= 30
       0  573.98    55.5  557.56   88.29545.0931   107.1  537.12   122.9  529.49
   126.9  528.48   150.7  528.11   166.5  525.55   178.4  527.18   186.4  526.43
   194.3  527.14   257.3   526.7     273  524.91   292.7  526.14  302.84  524.14
   304.5  523.95   316.3   524.1     332  525.36   347.7  524.22   379.2  525.72
   406.7  531.34   427.1532.9213   457.6  535.26  468.14537.0099   477.2  539.43
   488.9  540.81   492.8  542.64   496.7  546.03   504.5  550.72     528  562.36
#Mann= 6 ,-1 , 0
       0     .12       0   88.29     .12       0  302.84    .045       0
   316.3     .12       0   427.1    .016       0  468.14     .12       0
#XS Ineff= 2 , 0
          261.92  527.91
Permanent Ineff=
       F       F
Bank Sta=302.84,316.3
XS Rating Curve= 0 ,0
Exp/Cntr=0.3,0.1

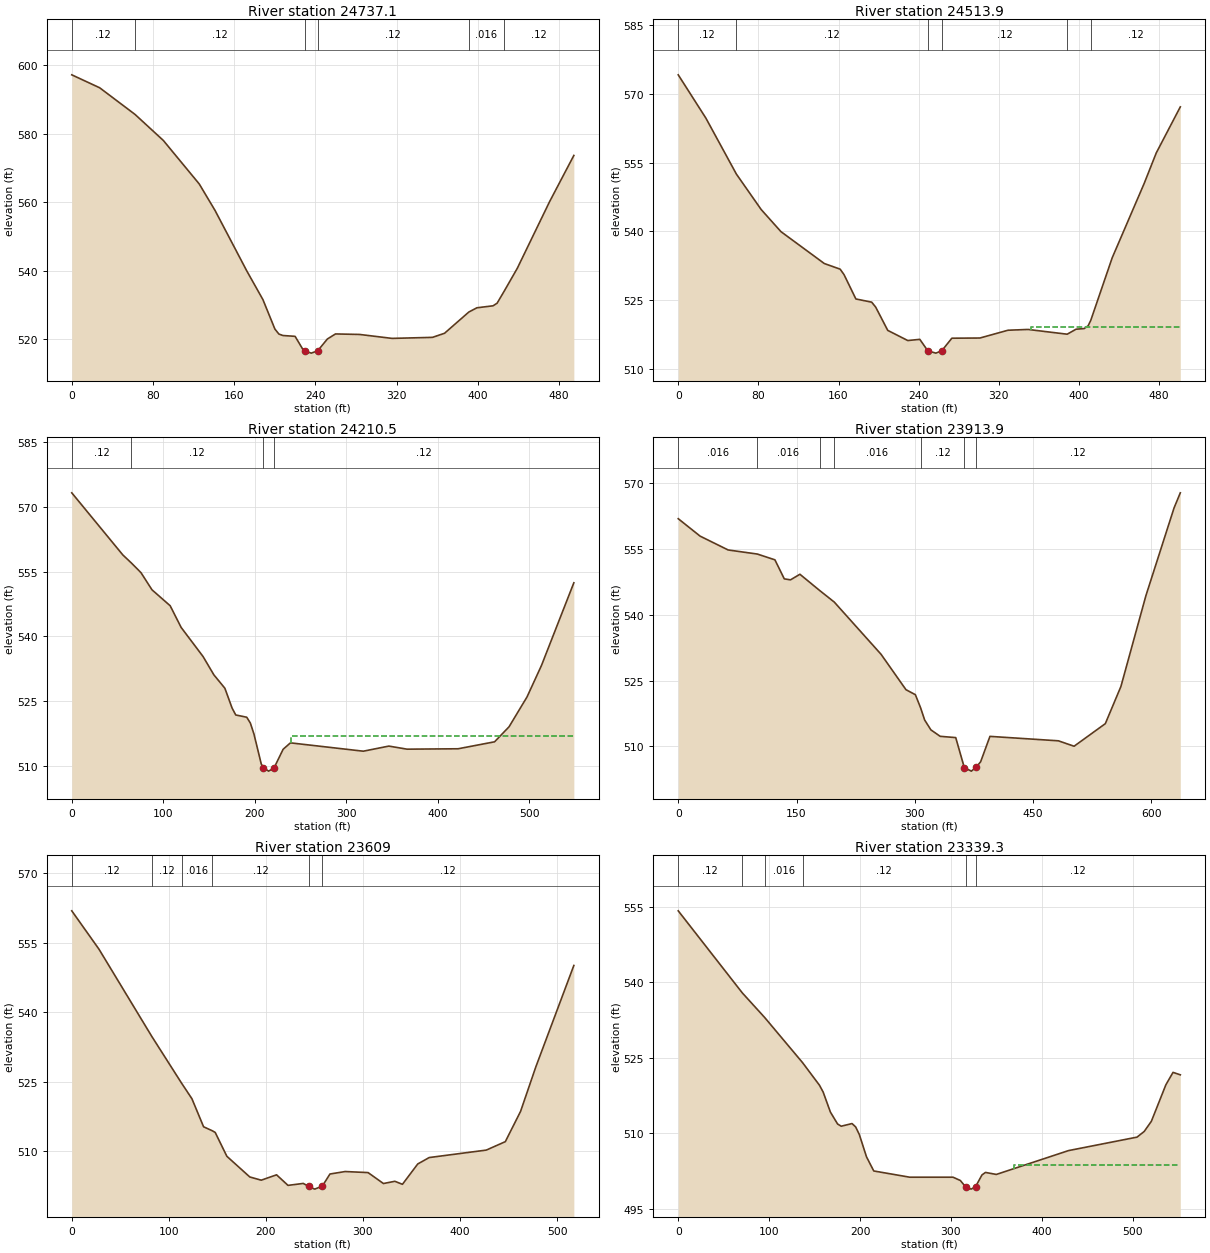
Type RM Length L Ch R = 1 ,24737.1 ,227.2,223.2,218.6
XS GIS Cut Line= 3
2369165.91980405 403996.94341509 2369122.2063088403797.646897674
2369081.28447464 403509.96407409
#Sta/Elev= 30
       0  597.16    27.5  593.38   62.23585.6263    90.2  578.01   125.6   565.3
   141.2  557.55   172.6  539.83   188.3  531.56   200.1  522.97     204  521.52
     208  521.08     220  520.84   227.9  516.91   229.5  516.59   235.9  515.94
  242.25  516.61   251.8  520.06   259.8  521.54   283.6  521.39   315.5  520.24
   355.3  520.54   367.2  521.73  391.14527.9285   399.1  529.17     415  529.75
     419  530.51  425.87533.9622   438.9   540.7   470.7  560.14   494.6  573.63
#Mann= 6 ,-1 , 0
       0     .12       0   62.23     .12       0   229.5    .045       0
  242.25     .12       0  391.14    .016       0  425.87     .12       0
Bank Sta=229.5,242.25
XS Rating Curve= 0 ,0
Exp/Cntr=0.3,0.1

Type RM Length L Ch R = 1 ,24513.9 ,295.1,303.4,306.9
XS GIS Cut Line= 3
2369385.97185738403964.3913148342369352.11759439403774.287036255
2369253.15945897403482.620296761
#Sta/Elev= 30
       0  574.18    27.6  564.72   58.04552.4995    82.8  544.75   102.5  539.93
   145.8  532.96   161.6  531.73   165.5  530.53   177.3  525.22   193.1  524.52
   197.1  523.43   209.1  518.36   229.1  516.14   241.1   516.4   249.1   513.9
   257.1  513.39  262.92  513.88   273.1  516.65   301.1  516.69   329.1  518.39
   349.1  518.56  388.19517.5236   397.1  518.62   405.1  518.75   409.1  519.36
  411.71520.5345   433.1   534.2   465.1  550.49   477.1  557.12   501.1  567.18
#Mann= 6 ,-1 , 0
       0     .12       0   58.04     .12       0   249.1    .045       0
  262.92     .12       0  388.19    .016       0  411.71     .12       0
#XS Ineff= 2 , 0
                           351.7           519.1
Permanent Ineff=
       F       F
Bank Sta=249.1,262.92
XS Rating Curve= 0 ,0
Exp/Cntr=0.3,0.1

Type RM Length L Ch R = 1 ,24210.5 ,298.3,296.6,294.7
XS GIS Cut Line= 3
2369612.31523672403956.7765006722369563.05516464403489.130782425
2369573.47181048403411.005938679
#Sta/Elev= 30
       0   573.2    55.8  558.84   64.75557.0533    75.7  554.73    87.7  550.77
   107.6  547.08   119.6  542.06   143.5  535.35   155.4  531.09   167.4     528
   175.3  523.41   179.3  521.81   191.3  521.29   195.3  519.93   199.2  517.41
   207.2  510.48  209.63  509.62   215.2  508.82   221.1  509.52   231.1  513.87
   239.1  515.36   318.8  513.43   346.7  514.61   366.6   513.9   422.4  513.99
   462.3   515.6   478.1  519.06   497.8  525.98   513.6  533.26     549  552.39
#Mann= 4 ,-1 , 0
       0     .12       0   64.75     .12       0  209.63    .045       0
   221.1     .12       0
#XS Ineff= 2 , 0
                          240.25          516.89
Permanent Ineff=
       F       F
Bank Sta=209.63,221.1
XS Rating Curve= 0 ,0
Exp/Cntr=0.3,0.1

Type RM Length L Ch R = 1 ,23913.9 ,303.3,304.9,306.4
XS GIS Cut Line= 4
 2369663.3154628 403943.558023172369893.14800839403762.201102421
2369859.12543863403579.9406401662369859.93022706403421.422584504
#Sta/Elev= 30
       0  561.78    27.7  557.82    63.3  554.67  100.33553.7422   122.6  552.43
   134.5   548.1   142.4  547.88   154.3  549.15  179.15545.4902  197.87542.8271
   257.2  530.96   288.8  522.91   300.7  521.78  307.28518.8286   312.5  516.02
   320.4  513.78   332.2  512.31   351.9  512.02   362.8   505.2   371.7   504.4
   377.8  505.28   383.5  506.53   395.3   512.3   482.1  511.29     502  510.06
   541.6  515.19   561.4  523.65   593.1   544.3   628.8  564.24   636.7  567.66
#Mann= 7 ,-1 , 0
       0    .016       0  100.33    .016       0  179.15     .12       0
  197.87    .016       0  307.28     .12       0   362.8    .045       0
   377.8     .12       0
Bank Sta=362.8,377.8
XS Rating Curve= 0 ,0
Exp/Cntr=0.3,0.1

Type RM Length L Ch R = 1 ,23609   ,265.7,269.7,272.3
XS GIS Cut Line= 4
2370210.19068138403908.4015974252370182.84690405403746.943258926
2370159.75672713403535.8252428472370173.73209289403395.380641833
#Sta/Elev= 30
       0  561.93      28  553.66   82.28534.8675   113.5 524.597   123.8  521.35
   135.8   515.3  144.85 514.424   147.8  514.07   159.8  508.92   183.4  504.46
   195.2  503.76     211  504.92   222.8  502.64   238.5  503.06  244.22   502.4
   250.3  501.83   258.2  502.49     266  505.09   281.7  505.63   305.3   505.4
   321.1  503.04   332.9  503.52   340.7  502.87   356.5  507.27   368.3  508.65
   427.1  510.26   446.7  512.08   462.4  518.61   478.1  528.21   517.3  550.13
#Mann= 6 ,-1 , 0
       0     .12       0   82.28     .12       0   113.5    .016       0
  144.85     .12       0  244.22    .045       0   258.2     .12       0
Bank Sta=244.22,258.2
XS Rating Curve= 0 ,0
Exp/Cntr=0.3,0.1

Type RM Length L Ch R = 1 ,23339.3 ,332.3,345.1,343
XS GIS Cut Line= 3
2370289.61768788403905.7976000012370430.24273472403782.099684671
2370447.16986622403417.516096264
#Sta/Elev= 30
       0  554.22   70.46537.9063   95.13533.0011  136.82524.0197   155.4  519.53
   159.4  518.19   167.4   514.2   175.3  511.83   179.3  511.39   191.2  511.92
   195.2  511.24   199.2  509.74   207.1   505.3   215.1  502.49   254.7  501.25
   302.3  501.25   310.3   500.6   316.1  499.34   322.2  498.88  327.03  499.35
   334.1   501.7     338   502.2   349.9   501.8   429.3  506.54   504.7  509.22
   512.6  510.35   520.5  512.38   536.4  519.62   544.3   522.1   552.3  521.61
#Mann= 6 ,-1 , 0
       0     .12       0   70.46     .12       0   95.13    .016       0
  136.82     .12       0   316.1    .045       0  327.03     .12       0
#XS Ineff= 2 , 0
                          369.66          503.72
Permanent Ineff=
       F       F
Bank Sta=316.1,327.03
XS Rating Curve= 0 ,0
Exp/Cntr=0.3,0.1

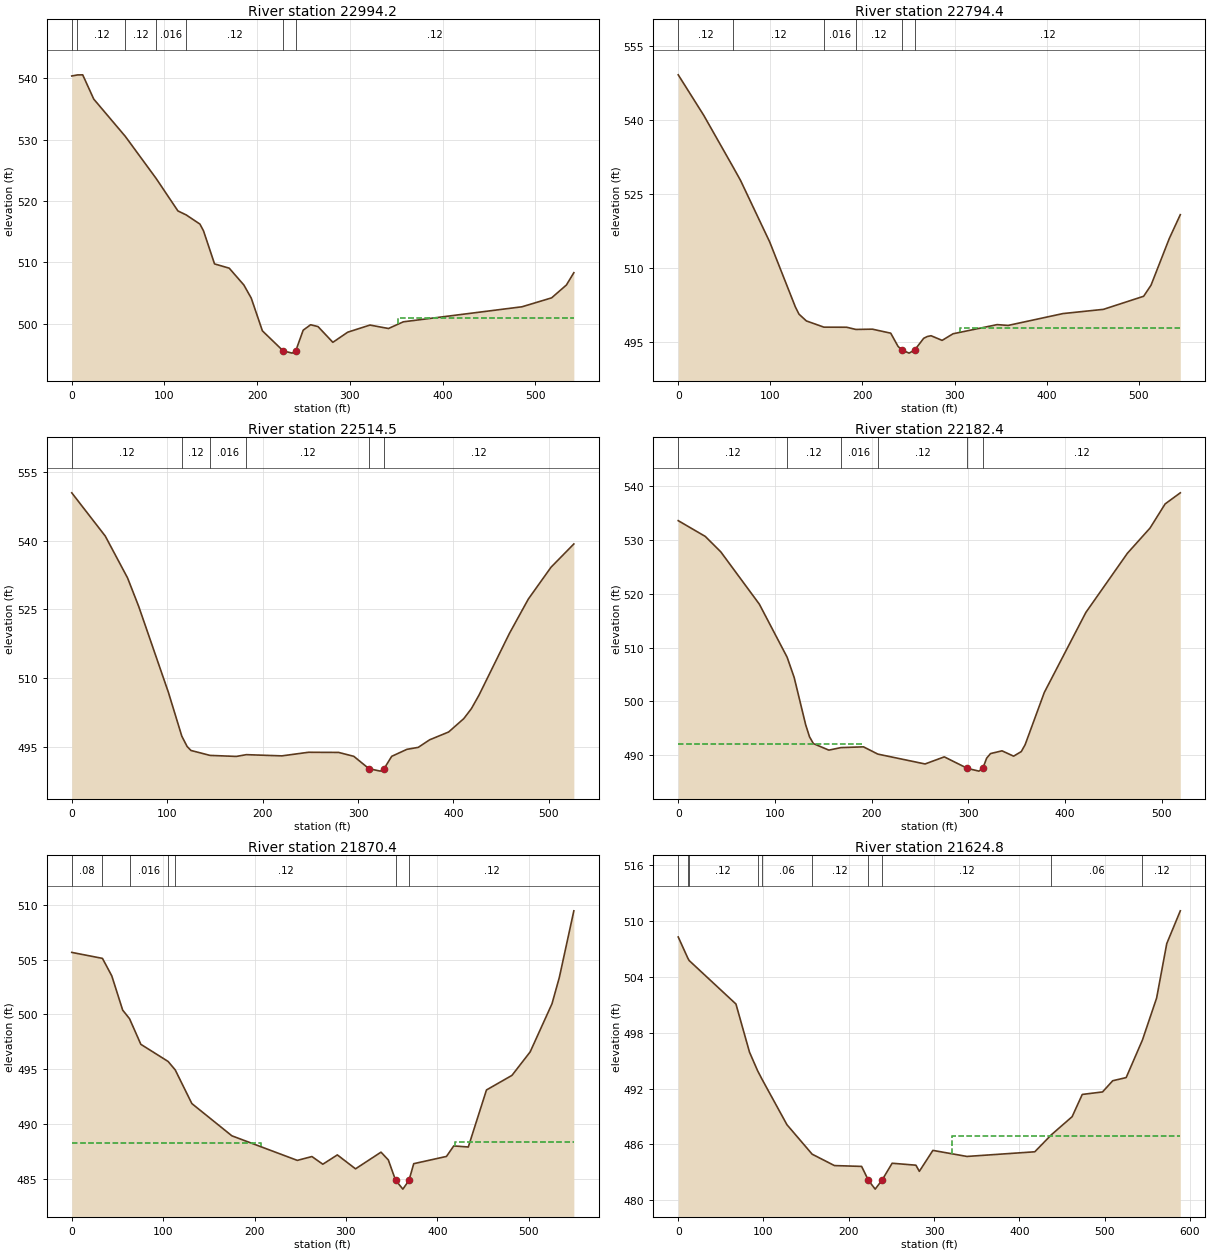
Type RM Length L Ch R = 1 ,22994.2 ,206.5,199.8,190.9
XS GIS Cut Line= 3
2370632.06549381403948.7663460972370672.43024246403771.683038846
2370652.89878547403412.307773337
#Sta/Elev= 30
       0  540.35    6.11540.5223    11.8  540.54    23.7  536.59   57.83530.4978
   91.08 523.641   114.5  518.37  123.46517.7184   138.2  516.23   142.1  515.12
     154  509.74   169.8  509.05   185.6  506.31   193.6  504.16   205.6  498.84
   227.9  495.59   237.6  495.21   241.6  495.59   249.6  498.95   257.6  499.83
   265.6  499.53   281.6  496.97   297.6  498.62   321.6  499.78   341.6  499.22
   357.6  500.31   485.6  502.76   517.5  504.21   533.5  506.31   541.5  508.31
#Mann= 7 ,-1 , 0
       0     .08       0    6.11     .12       0   57.83     .12       0
   91.08    .016       0  123.46     .12       0   227.9    .045       0
   241.6     .12       0
#XS Ineff= 2 , 0
                          352.32          500.95
Permanent Ineff=
       F       F
Bank Sta=227.9,241.6
XS Rating Curve= 0 ,0
Exp/Cntr=0.3,0.1

Type RM Length L Ch R = 1 ,22794.4 ,268.9,279.9,286.1
XS GIS Cut Line= 4
2370882.06564997403944.8598578422370884.32548797403785.929729506
2370819.56544688403593.2975688432370779.20102631 403414.91209884
#Sta/Elev= 30
       0  549.14    27.8  540.91   59.45530.5095    67.6  527.78    99.3  515.31
   127.2  502.14   131.1  500.69   139.1  499.32  158.17498.0564   182.9  498.04
  192.81497.5948   210.8  497.65   230.7  496.84   238.6  494.18   242.6  493.46
   250.6   492.8  256.77  493.45   266.5   495.8   270.5  496.17   274.5  496.32
   286.5  495.38   298.4  496.72   346.2  498.57   358.2  498.41   417.8  500.81
   461.6  501.66   505.3  504.31   513.3  506.55   533.1  515.99   545.1  520.83
#Mann= 6 ,-1 , 0
       0     .12       0   59.45     .12       0  158.17    .016       0
  192.81     .12       0   242.6    .045       0  256.77     .12       0
#XS Ineff= 2 , 0
                          305.88           497.8
Permanent Ineff=
       F       F
Bank Sta=242.6,256.77
XS Rating Curve= 0 ,0
Exp/Cntr=0.3,0.1

Type RM Length L Ch R = 1 ,22514.5 ,329,332.1,332.2
XS GIS Cut Line= 4
2371048.73231138403944.8598578422371093.55013514403836.870572507
2371100.81554055403586.7870831792371177.63854964403447.464199096
#Sta/Elev= 30
       0  550.39    35.1  540.98    58.5  531.86    70.2  525.64   101.3  506.95
  115.33497.4315   120.9  495.18   124.9  494.32  144.88493.2433   172.5  493.02
  182.94493.4039   220.2  493.14     248  493.92   279.7  493.89   295.6  493.04
   311.5  490.35   323.4  489.82   327.4  490.38   335.3  493.04   351.2  494.56
   363.1  494.99   375.1  496.64     395  498.34   410.9  501.26   418.8  503.41
   426.8  506.36   458.6  519.76   478.5  527.27   502.3   534.2   526.2  539.26
#Mann= 6 ,-1 , 0
       0     .12       0  115.33     .12       0  144.88    .016       0
  182.94     .12       0   311.5    .045       0   327.4     .12       0
Bank Sta=311.5,327.4
XS Rating Curve= 0 ,0
Exp/Cntr=0.3,0.1

Type RM Length L Ch R = 1 ,22182.4 ,308.8,312,309.8
XS GIS Cut Line= 4
2371400.29460038 403970.90147242 2371388.4950833403835.565457001
2371404.20108864403597.203729004 2371357.3258543403460.484842345
#Sta/Elev= 30
       0  533.57      28  530.64      44  527.78    83.9  518.06  112.56508.2345
   119.9  504.46   131.8  495.67   135.8  493.42   139.8  492.16   155.8  490.95
  168.29491.4202   191.6  491.56  206.43490.2121   255.3  488.38   275.2   489.7
   299.1  487.56     311  487.05     315  487.55     319  489.46     323  490.31
   334.9  490.82   346.9  489.83   354.8  490.68   358.8  491.96   378.6  501.65
   421.6  516.52   464.6  527.52     488   532.2   503.6  536.68   519.3  538.74
#Mann= 6 ,-1 , 0
       0     .12       0  112.56     .12       0  168.29    .016       0
  206.43     .12       0   299.1    .045       0     315     .12       0
#XS Ineff= 2 , 0
          190.09  492.06
Permanent Ineff=
       F       F
Bank Sta=299.1,315
XS Rating Curve= 0 ,0
Exp/Cntr=0.3,0.1

Type RM Length L Ch R = 1 ,21870.4 ,234.3,245.6,247.3
XS GIS Cut Line= 2
2371628.15930213403965.6931495072371664.61756255403417.516096264
#Sta/Elev= 30
       0  505.66   33.58505.1152    43.8  503.52    55.7   500.4    63.2499.6175
    75.6  497.28  105.37495.7217  113.21494.9483   131.4  491.88   175.2  488.94
   246.8   486.7   262.8  487.05   274.7  486.35   290.6   487.2   310.5  485.93
   338.4  487.45   346.4  486.74   354.3   484.9   362.3  484.08  368.96  484.87
   374.2   486.4     410  487.06     418  488.02   433.9  487.92   453.8  493.12
   481.7  494.45   501.6  496.59   525.5  500.98   533.5  503.37   549.4  509.45
#Mann= 7 ,-1 , 0
       0     .08       0   33.58     .06       0    63.2    .016       0
  105.37     .12       0  113.21     .12       0   354.3    .045       0
  368.96     .12       0
#XS Ineff= 2 , 0
          207.43  488.31   419.2          488.41
Permanent Ineff=
       F       F
Bank Sta=354.3,368.96
XS Rating Curve= 0 ,0
Exp/Cntr=0.3,0.1

Type RM Length L Ch R = 1 ,21624.8 ,104.4,110.4,115.9
XS GIS Cut Line= 3
2371769.58716889403941.8867666722371891.98324955403500.480497256
2371845.94003455403378.041437671
#Sta/Elev= 30
       0  508.28   11.16506.0285   12.77505.7552    67.7  501.08    83.6  495.91
   93.06493.9226   98.11493.0321   127.5  488.12  157.07484.9538   183.2  483.73
   215.1  483.64   223.1  482.14     231   481.2     239  482.16   250.9  483.98
   278.8  483.77   282.8  483.11   298.7  485.36   338.6  484.71   418.2  485.21
   437.5487.0252     462  488.98   473.9  491.37   497.7  491.64   509.6  492.84
   525.4  493.18  544.52497.2279   561.1  501.72     573  507.57   588.9  511.09
#Mann= 10 ,-1 , 0
       0    .016       0   11.16     .06       0   12.77     .12       0
   93.06     .12       0   98.11     .06       0  157.07     .12       0
   223.1    .045       0     239     .12       0   437.5     .06       0
  544.52     .12       0
#XS Ineff= 2 , 0
                          320.74          486.92
Permanent Ineff=
       F       F
Bank Sta=223.1,239
XS Rating Curve= 0 ,0
Exp/Cntr=0.3,0.1

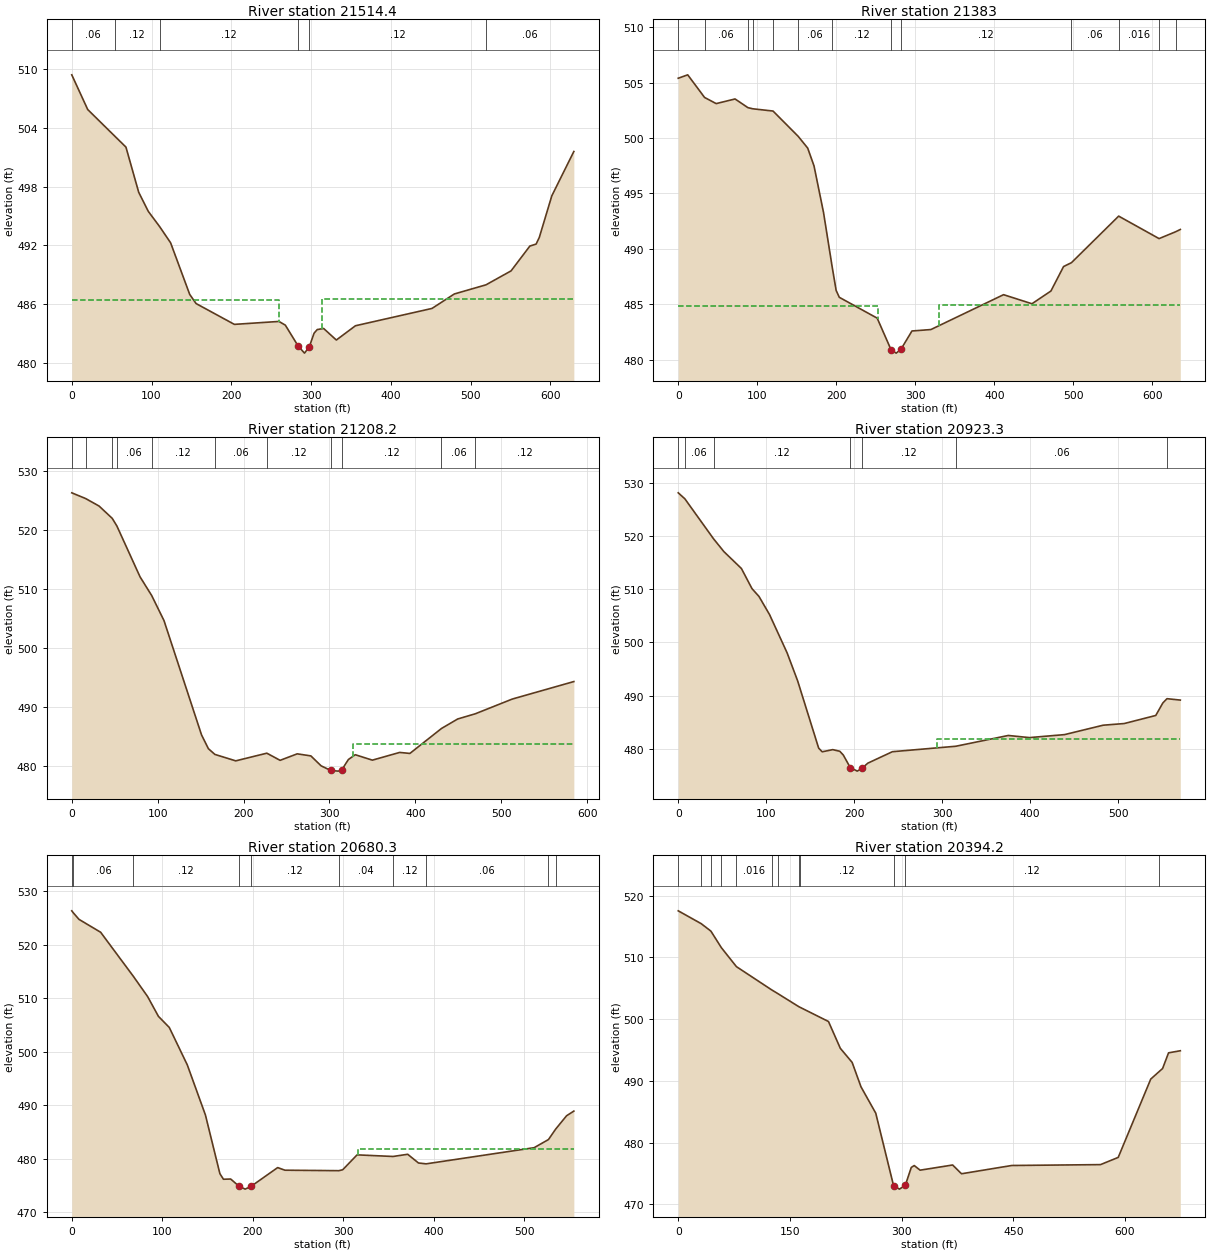
Type RM Length L Ch R = 1 ,21514.4 ,130.7,131.3,129.7
XS GIS Cut Line= 3
2371813.85807772   403954.9077382371992.24354772403492.668176919
2371932.74563521403372.833114758
#Sta/Elev= 30
       0  509.43      20  505.88   53.67 503.178    67.9  502.04    83.9  497.42
    95.9  495.47  110.29493.8909   123.9  492.25   147.8  486.98   155.8  486.04
   203.8  483.91   259.7  484.21   267.7  483.83   283.7   481.7   291.7  480.97
   297.7  481.61   303.7  483.01   307.7  483.38   315.7  483.49   331.6  482.31
   355.6  483.77   451.5  485.54   479.5  487.02  519.16487.9537   550.6  489.38
   574.2  491.92     582  492.12     586   492.8   601.7  497.06   629.3  501.59
#Mann= 6 ,-1 , 0
       0     .06       0   53.67     .12       0  110.29     .12       0
   283.7    .045       0   297.7     .12       0  519.16     .06       0
#XS Ineff= 2 , 0
          260.06  486.39  313.52          486.54
Permanent Ineff=
       F       F
Bank Sta=283.7,297.7
XS Rating Curve= 0 ,0
Exp/Cntr=0.3,0.1

Type RM Length L Ch R = 1 ,21383   ,188.4,174.8,159.7
XS GIS Cut Line= 3
2371948.78497322403949.4861609192372118.54546046403509.595308423
2372046.93110238403362.459775925
#Sta/Elev= 30
       0  505.41      12  505.72   33.29503.6787      48  503.12    71.9  503.54
   88.09502.7576   94.19502.6527  119.93502.4488  151.78500.1623   163.8   499.1
   171.8  497.49   183.8  493.29  194.89488.3127   199.8  486.24   203.8  485.62
   251.7  483.74  269.24  480.89   275.7  480.58   281.7  480.92   295.7  482.58
   319.7  482.71   411.6  485.86   447.5  485.04   471.5  486.19   487.5   488.4
   497.5488.7513  557.22492.9556  608.35490.9251  629.23491.5418   635.2  491.75
#Mann= 13 ,-1 , 0
       0     .12       0   33.29     .06       0   88.09    .016       0
   94.19    .016       0  119.93     .08       0  151.78     .06       0
  194.89     .12       0  269.24    .045       0   281.7     .12       0
   497.5     .06       0  557.22    .016       0  608.35     .08       0
  629.23     .06       0
#XS Ineff= 2 , 0
          252.12  484.86  330.13          484.97
Permanent Ineff=
       F       F
Bank Sta=269.24,281.7
XS Rating Curve= 0 ,0
Exp/Cntr=0.3,0.1

Type RM Length L Ch R = 1 ,21208.2 ,279.2,284.9,279
XS GIS Cut Line= 2
2372268.74529131 403907.613541262372122.45194872 403341.62648426
#Sta/Elev= 30
       0  526.33   16.05 525.368    31.8  524.09   47.13522.0012   52.57 520.699
    79.5  512.09   93.06 508.922   107.4  504.67   151.1   485.3   159.1  482.96
  166.62481.9951   190.9   480.9  227.11   482.2   242.6  480.99   262.5  482.09
   278.4  481.74   290.3  480.06   301.4  479.28   310.2  479.16   314.2  479.33
   322.1  481.13   330.1  481.94     350  481.02   381.8  482.33   393.7  482.16
   430.5  486.39   449.4     488  469.89488.8803     513  491.38   584.6  494.34
#Mann= 11 ,-1 , 0
       0     .08       0   16.05     .12       0   47.13     .12       0
   52.57     .06       0   93.06     .12       0  166.62     .06       0
  227.11     .12       0   301.4    .045       0   314.2     .12       0
   430.5     .06       0  469.89     .12       0
#XS Ineff= 2 , 0
                          326.93          483.78
Permanent Ineff=
       F       F
Bank Sta=301.4,314.2
XS Rating Curve= 0 ,0
Exp/Cntr=0.3,0.1

Type RM Length L Ch R = 1 ,20923.3 ,242.6,243,247.2
XS GIS Cut Line= 2
2372399.84476663403854.5851040042372368.97967088 403284.76865834
#Sta/Elev= 30
       0  528.11    7.52 526.988   40.14519.4672    51.9  517.06    71.8  513.89
    83.8  510.11    91.8  508.63   103.8  505.22   123.7  498.05   135.7  492.78
   159.6  480.13   163.6  479.44   175.6  479.85   183.6  479.54   187.6  478.83
   195.5  476.48   203.5  475.81  209.31  476.41   215.5  477.31   243.4  479.46
  315.54480.4861   375.1  482.51   399.1  482.11     439  482.67   482.9  484.44
   506.8  484.75   542.7  486.27   550.7  488.61  555.45 489.425   570.6  489.16
#Mann= 7 ,-1 , 0
       0     .06       0    7.52     .06       0   40.14     .12       0
   195.5    .045       0  209.31     .12       0  315.54     .06       0
  555.45    .016       0
#XS Ineff= 2 , 0
                          294.12          481.86
Permanent Ineff=
       F       F
Bank Sta=195.5,209.31
XS Rating Curve= 0 ,0
Exp/Cntr=0.3,0.1

Type RM Length L Ch R = 1 ,20680.3 ,289.4,286.1,279.2
XS GIS Cut Line= 2
2372620.78855047403822.754787087 2372518.7841613403277.759157926
#Sta/Elev= 30
       0  526.35    1.53526.0134       8  524.75    31.9  522.34   68.15514.0639
    83.8   510.3    95.7  506.61   107.7  504.53   127.6  497.52   147.6  488.16
   163.6  477.17   167.5  476.13   175.5  476.17   184.6  474.84   191.5  474.28
  198.11  474.81   227.4  478.31   235.4  477.82  294.97477.7319   299.2   477.9
   315.1  480.69  354.85  480.39     371   480.8   382.9  479.17  391.35 479.009
   510.6  482.03  526.46483.5532  534.47485.5224   546.5  488.01   554.5  488.88
#Mann= 10 ,-1 , 0
       0     .06       0    1.53     .06       0   68.15     .12       0
   184.6    .045       0  198.11     .12       0  294.97     .04       0
  354.85     .12       0  391.35     .06       0  526.46     .12       0
  534.47    .016       0
#XS Ineff= 2 , 0
                          316.41          481.76
Permanent Ineff=
       F       F
Bank Sta=184.6,198.11
XS Rating Curve= 0 ,0
Exp/Cntr=0.3,0.1

Type RM Length L Ch R = 1 ,20394.2 ,285.1,288.1,289.3
XS GIS Cut Line= 3
2372787.99720556403813.9861038332372897.69055572403723.505641758
2372720.72306189403221.538141757
#Sta/Elev= 30
       0  517.56    30.8 515.484   43.88514.2728   57.91511.5945   78.15 508.518
   125.5 504.754  133.39504.1776  162.34502.0021  162.97501.9691   201.8  499.63
   217.7  495.29   233.6     493   245.5  489.04   265.3  484.78   289.2  473.05
   297.1  472.47     305  473.08     313  475.98     317  476.29   324.9  475.54
   368.6  476.38   380.5  474.96     448   476.3   567.2  476.44     591  477.61
   634.7   490.3  646.31491.5529   650.6  492.01   658.6  494.55   674.4  494.89
#Mann= 12 ,-1 , 0
       0     .12       0    30.8     .08       0   43.88     .08       0
   57.91     .12       0   78.15    .016       0   125.5     .12       0
  133.39    .016       0  162.34     .08       0  162.97     .12       0
   289.2    .045       0     305     .12       0  646.31    .016       0
Bank Sta=289.2,305
XS Rating Curve= 0 ,0
Exp/Cntr=0.3,0.1