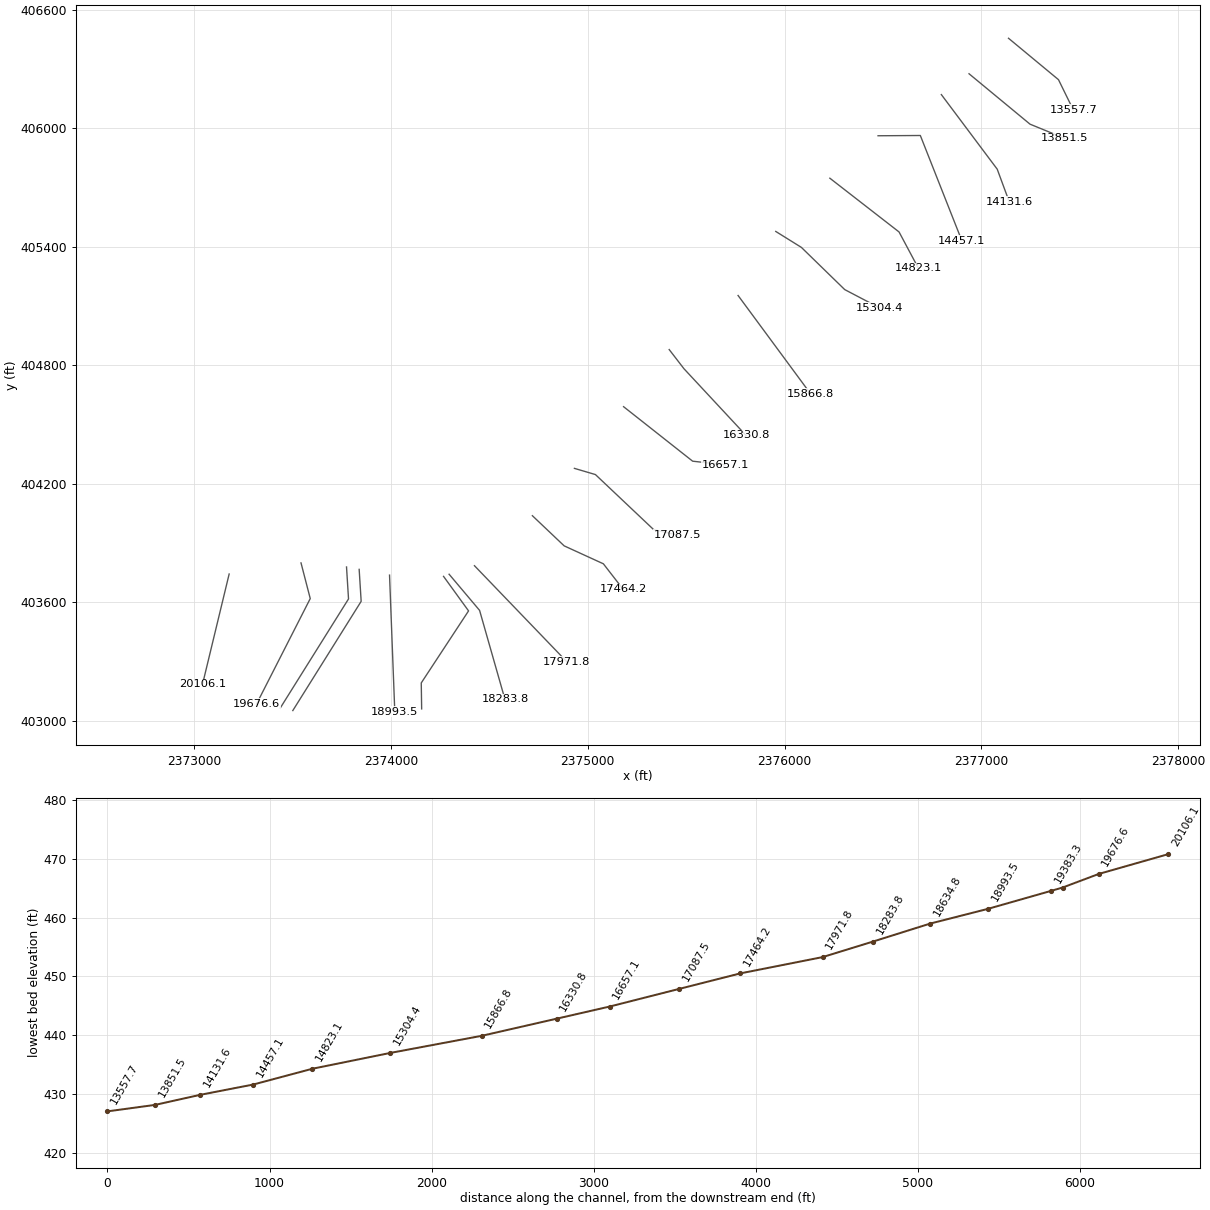
HEC-RAS study CHERRYRUN.prj: CHERRYRUN

--- CHERRYRUN.g01 (geometry) --- (continued)

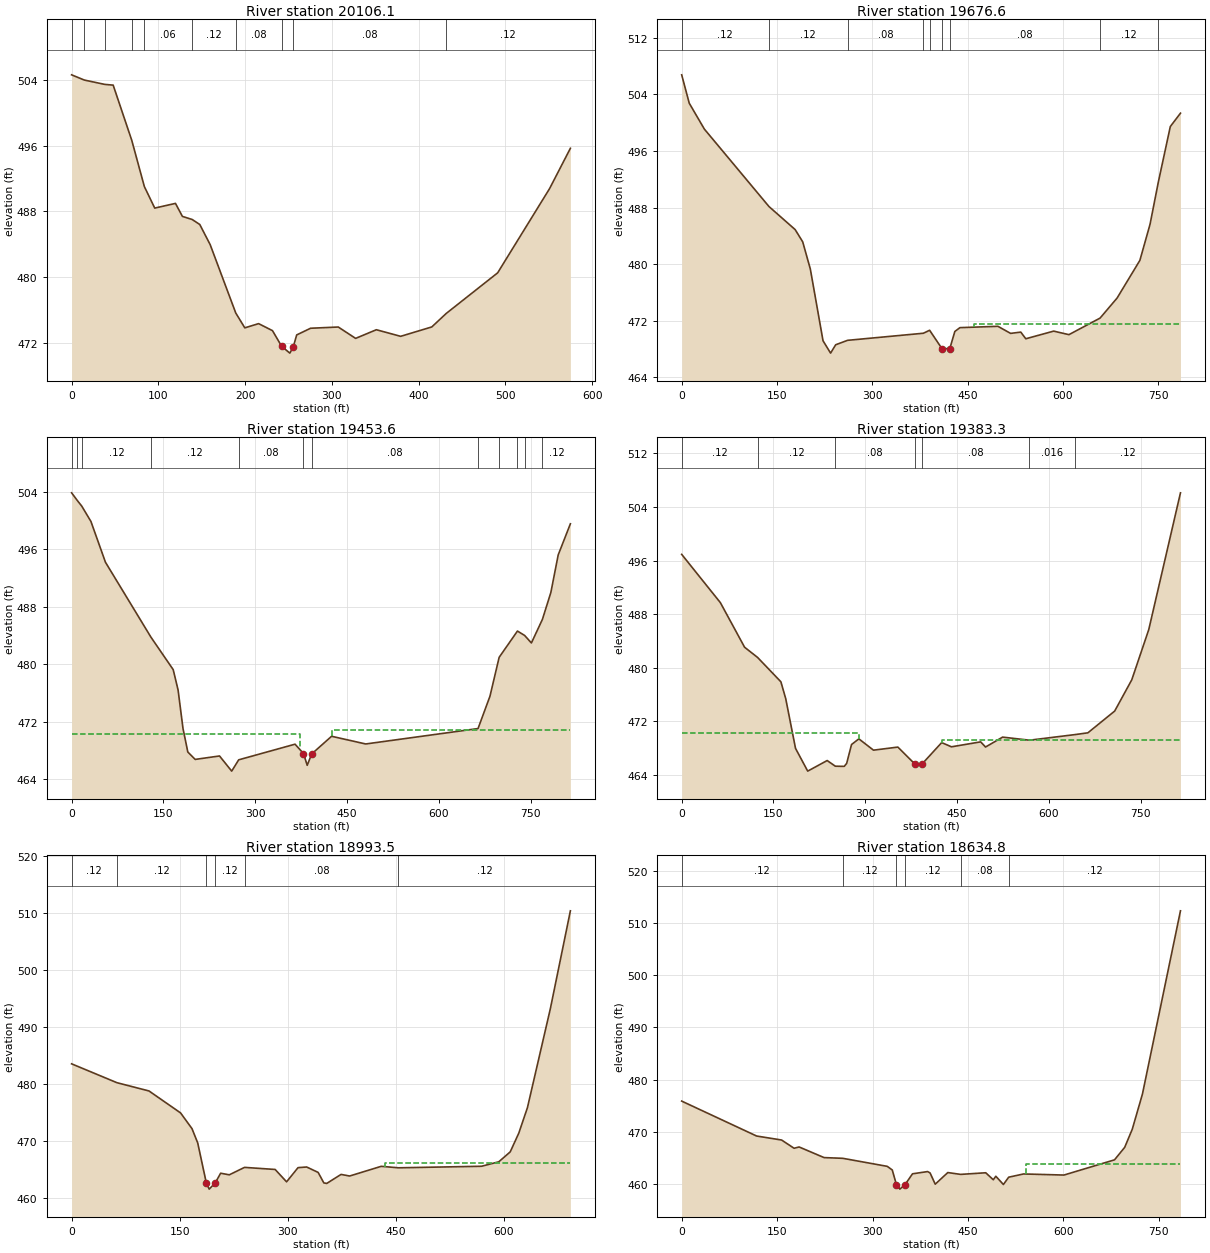
Type RM Length L Ch R = 1 ,20106.1 ,433.6,429.5,424.4
XS GIS Cut Line= 2
2373178.94064939403743.4711530062373043.52392547403184.877453923
#Sta/Elev= 30
       0  504.59   14.61503.9569   38.29503.4262    47.9  503.34   69.35496.6312
   83.85491.0224    95.8  488.41   119.7  488.98   127.7   487.4  138.93487.0258
   147.7  486.42   159.7  483.97  189.18475.6711   199.6  473.87   215.5  474.38
   231.5  473.53   242.1  471.62   251.5   470.8   255.4  471.55   259.4  473.01
   275.4  473.82   307.3  473.97   327.3  472.59   351.2  473.64   379.2  472.84
   415.1  473.98  431.72475.6166     491  480.55   550.8  490.77   574.8  495.67
#Mann= 10 ,-1 , 0
       0     .06       0   14.61    .016       0   38.29     .12       0
   69.35     .12       0   83.85     .06       0  138.93     .12       0
  189.18     .08       0   242.1    .045       0   255.4     .08       0
  431.72     .12       0
Bank Sta=242.1,255.4
XS Rating Curve= 0 ,0
Exp/Cntr=0.3,0.1

Type RM Length L Ch R = 1 ,19676.6 ,225.1,223,217
XS GIS Cut Line= 3
2373543.97961746403799.6993870142373590.85452372403619.143973842
2373318.28518696403086.157835096
#Sta/Elev= 30
       0  506.76    11.9  502.75    35.7  499.09  137.41488.1466   178.6  484.89
   190.5  483.16   202.5  479.32   222.5  469.18   234.4  467.43   242.4  468.61
  261.15469.2387  380.44470.2393  390.31470.6611   409.6  468.08     422  468.05
     430  470.49     438  471.03   497.8  471.22   517.8  470.22   533.8   470.4
   541.7  469.46   585.6  470.54   609.6  470.04  658.63472.3806   685.4  475.21
   721.3  480.54   737.3  485.64  750.23491.5548   769.2  499.45   785.2  501.34
#Mann= 9 ,-1 , 0
       0     .12       0  137.41     .12       0  261.15     .08       0
  380.44     .12       0  390.31     .08       0   409.6    .045       0
     422     .08       0  658.63     .12       0  750.23    .016       0
#XS Ineff= 2 , 0
                          460.68          471.57
Permanent Ineff=
       F       F
Bank Sta=409.6,422
XS Rating Curve= 0 ,0
Exp/Cntr=0.3,0.1

Type RM Length L Ch R = 1 ,19453.6 ,259.5,70.3,62.9
XS GIS Cut Line= 3
2373775.14221288403779.1367640942373785.29901671403617.407756835
2373438.07694213 403064.45643492
#Sta/Elev= 30
       0  503.86    9.54502.7678   16.63502.0066    31.6  499.87    55.3   494.2
   129.7483.7598     166  479.25     174  476.41     182  471.06   189.9  467.78
   201.9  466.75   241.7  467.23   261.6  465.12     273466.6925   365.1  468.87
  378.85  467.57     385  465.93   392.3  467.51   424.8  469.97   480.6   468.9
  664.11471.0464   683.6  475.55  698.61480.9619   728.5484.6168  740.19484.0087
   751.3  482.96  769.27486.2399   783.1  489.99   795.1  495.22     815  499.55
#Mann= 12 ,-1 , 0
       0     .12       0    9.54     .08       0   16.63     .12       0
   129.7     .12       0     273     .08       0  378.85    .045       0
   392.3     .08       0  664.11     .06       0  698.61    .016       0
   728.5     .12       0  740.19    .016       0  769.27     .12       0
#XS Ineff= 2 , 0
          372.55  470.22  426.21          470.81
Permanent Ineff=
       F       F
Bank Sta=378.85,392.3
XS Rating Curve= 0 ,0
Exp/Cntr=0.3,0.1

Type RM Length L Ch R = 1 ,19383.3 ,181,389.8,409.8
XS GIS Cut Line= 3
2373839.37732063403766.9976807532373849.53510872403605.254894003
2373502.31303413403052.303572088
#Sta/Elev= 30
       0  496.93    63.2  489.72   102.8  483.06  123.98481.5405   162.1   477.9
     170  475.38     186  467.96   205.9  464.56   237.7  466.14  251.04 465.296
   265.6  465.27   269.6  465.72   277.5  468.53   289.5  469.38   313.4  467.69
   353.2  468.15     381  465.62     393  465.65   424.8  468.82   440.8  468.19
   488.5  468.93   496.5  468.16   524.4  469.64   568.3469.1769  643.15470.0213
   663.7  470.28   707.5  473.53   735.4  478.19   763.2   485.7     815  506.12
#Mann= 7 ,-1 , 0
       0     .12       0  123.98     .12       0  251.04     .08       0
     381    .045       0     393     .08       0   568.3    .016       0
  643.15     .12       0
#XS Ineff= 2 , 0
          288.96  470.22  425.18          469.21
Permanent Ineff=
       F       F
Bank Sta=381,393
XS Rating Curve= 0 ,0
Exp/Cntr=0.3,0.1

Type RM Length L Ch R = 1 ,18993.5 ,371.5,358.7,341.7
XS GIS Cut Line= 2
2373993.66277322403737.8415710932374020.36842847 403046.22714068
#Sta/Elev= 30
       0  483.48   62.83480.1734   107.4  478.72   151.2  474.87   167.1   472.1
     175   469.6     187  462.55   190.9   461.5   199.2  462.57   206.8  464.29
   218.8  464.01  239.94465.3132   282.4  464.95   298.3  462.78   314.2  465.27
   326.2  465.38   342.1  464.43     350  462.59     354   462.5   373.9  464.08
   385.8   463.8   429.6   465.5   453.5  465.24   568.8  465.51   592.7  466.29
   608.6  468.03   620.5  471.32   632.5  475.79   664.3  493.15   692.1  510.32
#Mann= 6 ,-1 , 0
       0     .12       0   62.83     .12       0     187    .045       0
   199.2     .12       0  239.94     .08       0   453.5     .12       0
#XS Ineff= 2 , 0
                          434.88          466.08
Permanent Ineff=
       F       F
Bank Sta=187,199.2
XS Rating Curve= 0 ,0
Exp/Cntr=0.3,0.1

Type RM Length L Ch R = 1 ,18634.8 ,325.9,350.9,372.2
XS GIS Cut Line= 4
2374268.03197514403731.5207175912374395.08651105403556.838980347
 2374154.8163223403192.2645782532374156.80516347403060.745484337
#Sta/Elev= 30
       0  475.87   117.8  469.17   157.1   468.4   176.7  466.82   184.6  467.07
   223.9  465.03  253.29464.8923   323.2  463.35   331.1  462.65  337.65  459.81
     343  458.98     351  459.82   362.9  461.92   386.7  462.35   390.6  462.07
   398.6  459.93   418.4  462.16  438.63461.8082     478  462.12   489.9  460.78
   493.9  461.45   505.8  459.87   514.1  461.27   537.5  461.89     601  461.68
   680.5   464.6   696.5     467   708.4  470.47   724.4  477.22   784.2  512.38
#Mann= 6 ,-1 , 0
       0     .12       0  253.29     .12       0  337.65    .045       0
     351     .12       0  438.63     .08       0   514.1     .12       0
#XS Ineff= 2 , 0
                          540.76          463.72
Permanent Ineff=
       F       F
Bank Sta=337.65,351
XS Rating Curve= 0 ,0
Exp/Cntr=0.3,0.1

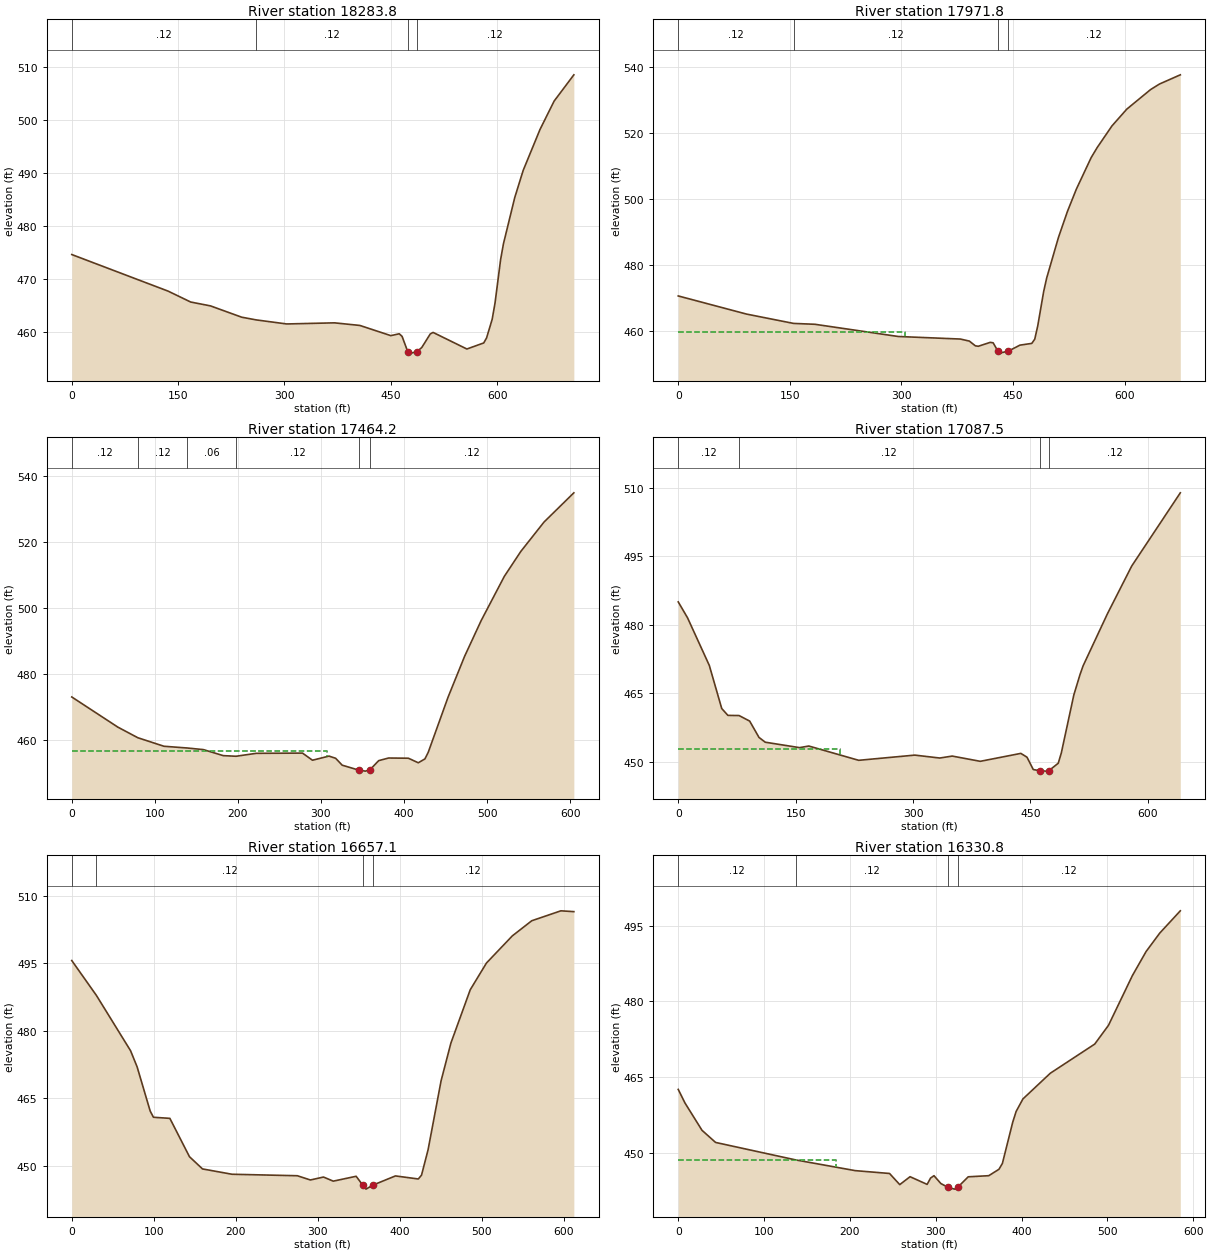
Type RM Length L Ch R = 1 ,18283.8 ,300.1,312,323.3
XS GIS Cut Line= 3
2374296.24386097403742.3714176712374451.07590039403559.443305835
2374579.98213863403108.922553346
#Sta/Elev= 30
       0   474.6   135.8  467.68   167.8  465.61   195.7  464.88   239.7  462.74
  260.32462.2252   303.2  461.46   370.7  461.67   406.4  461.18   450.1  459.25
     462   459.6     466  459.11     474  456.21   477.9  455.94   486.6  456.17
   493.8  457.01   505.7  459.56   509.7  459.86   557.4  456.72   581.2  457.87
   585.2  458.82   593.1  462.35   597.1  465.41     605  473.66     609  476.64
   624.9  485.37   636.8  490.51   660.6  498.28   680.5  503.64   708.3  508.61
#Mann= 4 ,-1 , 0
       0     .12       0  260.32     .12       0     474    .045       0
   486.6     .12       0
Bank Sta=474,486.6
XS Rating Curve= 0 ,0
Exp/Cntr=0.3,0.1

Type RM Length L Ch R = 1 ,17971.8 ,498.8,507.7,515.7
XS GIS Cut Line= 2
 2374425.0342858403785.5717905912374893.78433256403299.894612342
#Sta/Elev= 30
       0  470.64    91.9  465.13  155.05462.3025   183.7  462.04   295.6  458.34
   379.4  457.56   391.4  456.94   399.4  455.51   403.4  455.37   419.4  456.55
   423.4  456.42  429.74  453.89   431.4  453.29   443.3  453.83   459.3  455.71
   475.3  456.24   479.3  457.52   483.3  461.52   491.3  471.98   495.3  476.04
   511.2  488.41   523.2  496.24   535.2  503.02   555.2  512.63   563.2  515.64
   583.1  522.22   603.1  527.32     635  533.24     647  534.93     675  537.72
#Mann= 4 ,-1 , 0
       0     .12       0  155.05     .12       0  429.74    .045       0
   443.3     .12       0
#XS Ineff= 2 , 0
          304.85  459.76
Permanent Ineff=
       F       F
Bank Sta=429.74,443.3
XS Rating Curve= 0 ,0
Exp/Cntr=0.3,0.1

Type RM Length L Ch R = 1 ,17464.2 ,384.7,376.6,368.5
XS GIS Cut Line= 4
2374719.30502272 404038.609998422374880.66592047403886.009909928
2375079.98212288 403795.120327922375180.24274914403666.214089677
#Sta/Elev= 30
       0  472.98    55.5  463.84   79.55460.6325     111  458.05  138.72 457.529
   158.6  457.03   182.4  455.21  197.75455.0227   222.1  455.91   277.8  455.98
   289.8  453.82   309.7  455.07   317.7  454.41   325.6  452.32   345.8  450.81
   353.5  450.52  358.94   450.9   369.5  453.69   381.4  454.49   405.3  454.43
   417.2  453.05   425.2  454.22   429.2  456.23   453.1  472.94     473   485.3
   492.9   496.1   520.8   509.5   540.7  517.07   568.6  525.95   604.5   534.8
#Mann= 6 ,-1 , 0
       0     .12       0   79.55     .12       0  138.72     .06       0
  197.75     .12       0   345.8    .045       0  358.94     .12       0
#XS Ineff= 2 , 0
          307.74  456.55
Permanent Ineff=
       F       F
Bank Sta=345.8,358.94
XS Rating Curve= 0 ,0
Exp/Cntr=0.3,0.1

Type RM Length L Ch R = 1 ,17087.5 ,427.7,430.4,432.4
XS GIS Cut Line= 4
2374932.84691846 404278.193180682375039.50615397404246.904857427
2375335.19060197 403968.29747501 2375456.2841918403940.953697667
#Sta/Elev= 30
       0  484.99    11.9   481.5    39.7  471.07    55.6  461.61    63.5  460.11
   77.72 460.075    91.3  458.86   103.2  455.28   111.2  454.23     155  453.04
   166.9  453.39   230.6  450.26   302.3   451.4   334.2  450.76   350.1  451.19
     386  450.04   437.8  451.78   445.7  450.94   453.7  448.24   461.7  447.98
   469.6  447.89   473.6  447.98   485.6  449.62   489.5  451.84   505.5  464.57
   513.4  469.04   517.4  470.98   548.4  482.36   579.5  492.85   641.6   508.9
#Mann= 4 ,-1 , 0
       0     .12       0   77.72     .12       0   461.7    .045       0
   473.6     .12       0
#XS Ineff= 2 , 0
           206.6  452.65
Permanent Ineff=
       F       F
Bank Sta=461.7,473.6
XS Rating Curve= 0 ,0
Exp/Cntr=0.3,0.1

Type RM Length L Ch R = 1 ,16657.1 ,328.5,326.4,323.7
XS GIS Cut Line= 3
2375182.52850571404590.4619130942375533.43134722404314.571388751
2375698.15345871404296.190848097
#Sta/Elev= 30
       0  495.59   30.07487.8475    71.7  475.58    79.7  471.99    95.6   462.2
    99.6  460.82   119.6  460.58   143.5  452.07   159.4  449.36   195.3  448.18
     275  447.85   290.9  446.91   306.9  447.56   318.8  446.65   346.7  447.73
   354.7  445.78   358.7  444.88     367  445.76   394.6  447.81   422.5  447.13
   426.4  447.98   434.4  453.62   450.3  468.95   462.2  477.27   485.8  489.11
   505.6  495.05   537.1  501.06   560.8  504.42   596.3  506.62   612.1  506.44
#Mann= 4 ,-1 , 0
       0     .12       0   30.07     .12       0   354.7    .045       0
     367     .12       0
Bank Sta=354.7,367
XS Rating Curve= 0 ,0
Exp/Cntr=0.3,0.1

Type RM Length L Ch R = 1 ,16330.8 ,460.8,464,458.5
XS GIS Cut Line= 3
2375414.29936764404879.524327084 2375489.3018423404782.514350504
2375804.92424256404444.628543347
#Sta/Elev= 30
       0  462.57     7.9  459.87    27.7  454.47    43.5  452.07  136.99448.6001
   206.3  446.48   246.2  445.92   258.1  443.71   270.1  445.28     290  443.76
     294  445.01     298  445.48     306  443.93     314   443.2   321.9  442.82
   325.9  443.23   337.9  445.26   361.8  445.48   373.7  446.75   377.7  447.91
   389.7  456.05   393.7   458.2   401.6  460.68   433.5  465.77   485.3  471.55
   501.3  475.26   529.2  485.12   545.1  489.87   561.1  493.54     585  497.94
#Mann= 4 ,-1 , 0
       0     .12       0  136.99     .12       0     314    .045       0
   325.9     .12       0
#XS Ineff= 2 , 0
           183.9  448.61
Permanent Ineff=
       F       F
Bank Sta=314,325.9
XS Rating Curve= 0 ,0
Exp/Cntr=0.3,0.1

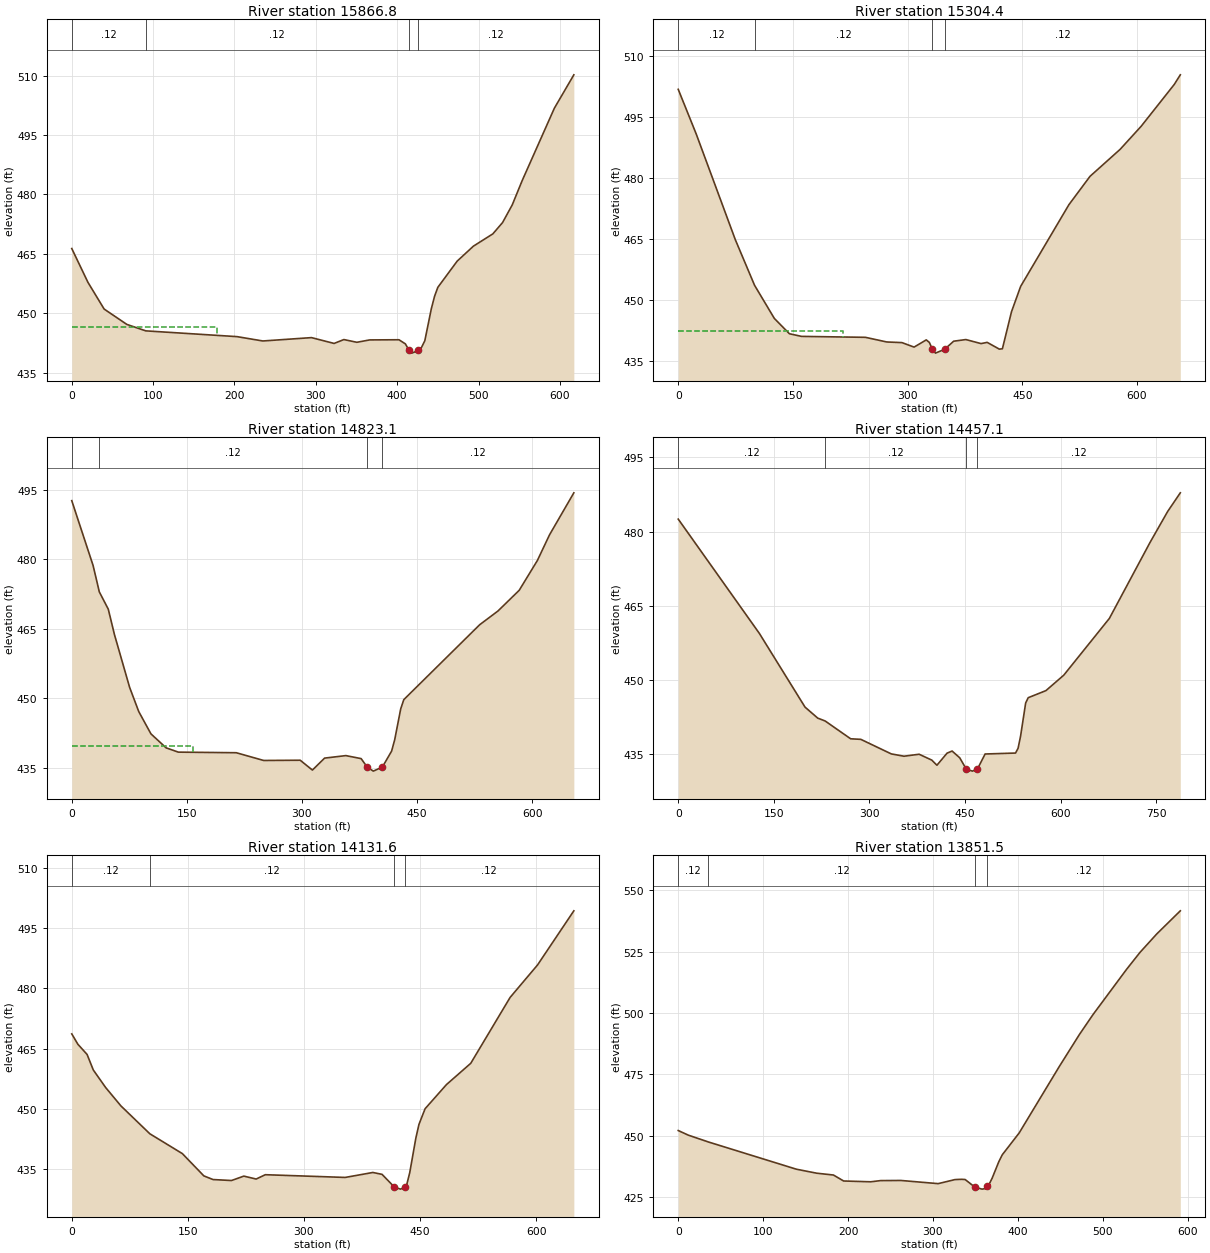
Type RM Length L Ch R = 1 ,15866.8 ,556.8,562.4,564.6
XS GIS Cut Line= 2
2375764.22714546405153.1933991762376131.41440322404657.099575087
#Sta/Elev= 30
       0  466.34    19.9  457.79    39.8  451.04    67.7  447.16   90.97445.5278
   203.1  444.07   234.9  442.97   294.7  443.82   322.5  442.35   334.5  443.33
   350.4  442.64   366.3  443.24   402.2  443.28   410.1  442.24   414.1  440.78
   418.1   439.9   426.1  440.62     430  441.37     434  443.03     442  451.11
     446  454.28     450  456.53   473.8  463.16   493.8  466.95   517.6  470.04
   529.6  472.91   541.5  477.38   553.5  483.42   593.3  501.83   617.2  510.25
#Mann= 4 ,-1 , 0
       0     .12       0   90.97     .12       0   414.1    .045       0
   426.1     .12       0
#XS Ineff= 2 , 0
          178.43  446.57
Permanent Ineff=
       F       F
Bank Sta=414.1,426.1
XS Rating Curve= 0 ,0
Exp/Cntr=0.3,0.1

Type RM Length L Ch R = 1 ,15304.4 ,475,481.2,486.5
XS GIS Cut Line= 4
2375955.63325872405477.4119108472376085.84165972405396.682741597
2376305.89371306405183.1411739292376480.37302288 405091.99535884
#Sta/Elev= 30
       0  501.76    23.6  490.76    74.6  464.88   99.82453.6569   125.7  445.52
   145.4  441.76   161.2  441.11   244.8  440.88   272.7  439.74   292.6  439.58
   308.5  438.48   324.4  440.25   328.4  439.64   332.4  437.96   336.4     437
   348.3  437.93   360.3  439.93   376.2  440.33   396.1  439.34   404.1  439.64
     420  437.98     424  438.07   435.9  447.16   447.9   453.4     511  473.44
   538.6   480.4     578  487.03   605.5  492.69   648.8  502.96   656.7  505.32
#Mann= 4 ,-1 , 0
       0     .12       0   99.82     .12       0   332.4    .045       0
   348.3     .12       0
#XS Ineff= 2 , 0
             216  442.43
Permanent Ineff=
       F       F
Bank Sta=332.4,348.3
XS Rating Curve= 0 ,0
Exp/Cntr=0.3,0.1

Type RM Length L Ch R = 1 ,14823.1 ,378.6,366,352.3
XS GIS Cut Line= 3
2376230.37286672405746.943195924 2376581.9354838405474.807913423
2376680.89361922405289.911957756
#Sta/Elev= 30
       0  492.69    27.8  478.69   35.92472.9926    47.6  469.26    55.6   463.8
    75.4  452.39    87.3  447.16   103.2  442.35     123  439.33   138.9  438.41
   214.4  438.28   250.1  436.61   297.7  436.66   313.6  434.54   329.5  437.12
   357.2  437.66   377.1  437.01     385  435.18     393  434.31   404.8   435.2
   416.8  438.63   420.8  441.05   428.7  447.76   432.7  449.74   531.6  465.91
   555.4  468.87   583.1  473.34   606.8  479.78   622.6  485.31   654.3  494.38
#Mann= 4 ,-1 , 0
       0     .12       0   35.92     .12       0     385    .045       0
   404.8     .12       0
#XS Ineff= 2 , 0
           158.2   439.7
Permanent Ineff=
       F       F
Bank Sta=385,404.8
XS Rating Curve= 0 ,0
Exp/Cntr=0.3,0.1

Type RM Length L Ch R = 1 ,14457.1 ,313.7,325.5,334.6
XS GIS Cut Line= 3
2376475.16437188405961.7869263442376690.00843039405963.089089096
2376900.94567256 405430.53700459
#Sta/Elev= 30
       0  482.52   127.3  459.43   198.9  444.55   218.8  442.33  230.45441.7496
   270.5  438.15   286.4  438.04   334.2   435.1   354.1  434.63   377.9  435.03
   397.8  433.84   405.8  432.81   421.7  435.25   429.6  435.68   441.6  434.31
  451.96     432   461.5  431.62   469.4  432.06   481.4  435.08   529.1  435.27
   533.1  436.23     537  438.66     545  445.38     549  446.45   576.8  447.88
   604.7  450.99   676.3  462.46   739.9  477.76   767.8  484.07   787.6  487.83
#Mann= 4 ,-1 , 0
       0     .12       0  230.45     .12       0  451.96    .045       0
   469.4     .12       0
Bank Sta=451.96,469.4
XS Rating Curve= 0 ,0
Exp/Cntr=0.3,0.1

Type RM Length L Ch R = 1 ,14131.6 ,274.4,280.1,284.4
XS GIS Cut Line= 3
2376796.77921422406170.120499179 2377080.6333053405792.516267508
2377141.83134563405627.151768833
#Sta/Elev= 30
       0  468.66     7.9  466.07    19.8  463.52    27.8  459.65    43.7  455.28
    63.5  450.67  100.87443.7084   142.9  438.75   170.7  433.18   182.6  432.27
   206.4  432.03   222.3  433.13   238.2   432.4   250.1  433.48   353.3   432.8
     389  434.04   400.9  433.57   416.8   430.4   424.8  429.88  430.31  430.39
   432.7  430.93   436.7  434.02   444.6  442.66   448.6  446.06   456.5  449.96
   484.2  456.01   515.5  461.31   566.4  477.78   601.7  485.85   648.7   499.4
#Mann= 4 ,-1 , 0
       0     .12       0  100.87     .12       0   416.8    .045       0
  430.31     .12       0
Bank Sta=416.8,430.31
XS Rating Curve= 0 ,0
Exp/Cntr=0.3,0.1

Type RM Length L Ch R = 1 ,13851.5 ,283.6,293.8,285.8
XS GIS Cut Line= 3
2376937.40426105406275.5891202542377247.29996672406020.380641177
2377423.08111122405948.766283095
#Sta/Elev= 30
       0  452.06    11.9  450.17   35.59447.3878   139.1  436.29     163  434.66
   182.8  433.91   194.8  431.48   226.6  431.15   238.5  431.64   262.3  431.69
   306.1   430.4   325.9  432.05   333.9  432.17   337.9  432.07   349.2  429.02
   357.7  428.16   361.7  428.36   364.2  429.28   365.7  429.84   369.7  432.63
   377.6  439.38   381.6  442.15   401.5  451.06   448.9  478.24   472.6  491.29
   488.4  499.31     528   517.8   543.8  524.71   563.6  532.25   591.3  541.67
#Mann= 4 ,-1 , 0
       0     .12       0   35.59     .12       0   349.2    .045       0
   364.2     .12       0
Bank Sta=349.2,364.2
XS Rating Curve= 0 ,0
Exp/Cntr=0.3,0.1

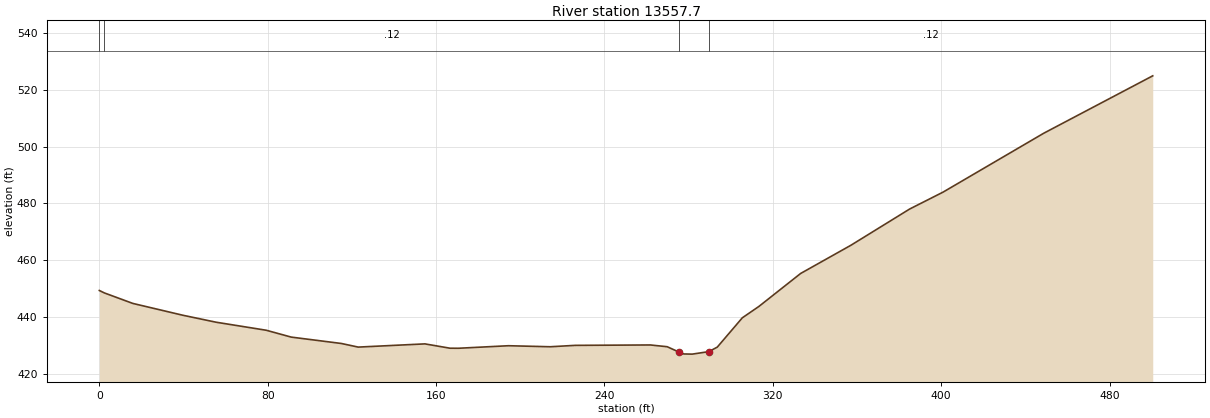
Type RM Length L Ch R = 1 ,13557.7 ,272.7,263.3,260
XS GIS Cut Line= 3
2377137.92485738406455.2767530082377391.83117372406245.641345501
2377467.35202006406091.995327339
#Sta/Elev= 30
       0  449.42    2.44448.5538    15.9  444.88    39.7  440.72    55.5  438.27
    79.3  435.45    91.2  433.04     115   430.8     123  429.53   154.7  430.66
   166.6  429.14   170.6  429.12   194.4  430.01   214.2  429.65   226.1  430.14
   261.8  430.28   269.8  429.66  275.21  427.85   277.7  427.12   281.7  427.06
   289.6  427.94   293.6  429.52   305.5  439.82   313.4  443.83   333.2   455.4
   357.1  465.32     385  478.05   400.9     484   448.7  504.68   500.5  524.86
#Mann= 4 ,-1 , 0
       0     .12       0    2.44     .12       0  275.21    .045       0
   289.6     .12       0
Bank Sta=275.21,289.6
XS Rating Curve= 0 ,0
Exp/Cntr=0.3,0.1