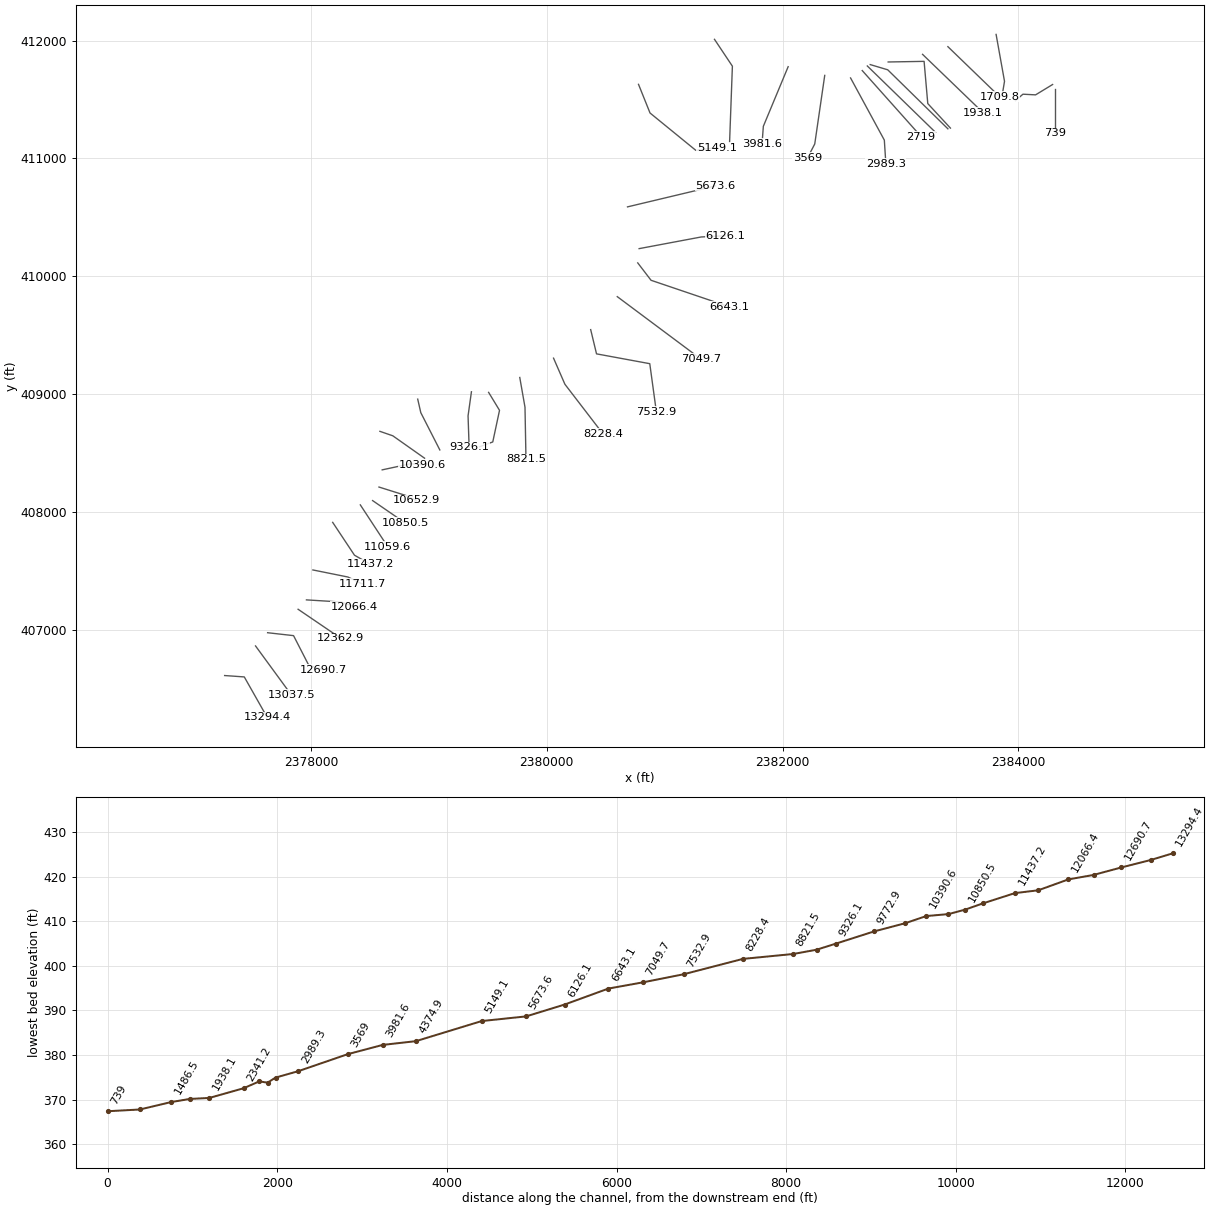
HEC-RAS study CHERRYRUN.prj: CHERRYRUN

--- CHERRYRUN.g01 (geometry) --- (continued)

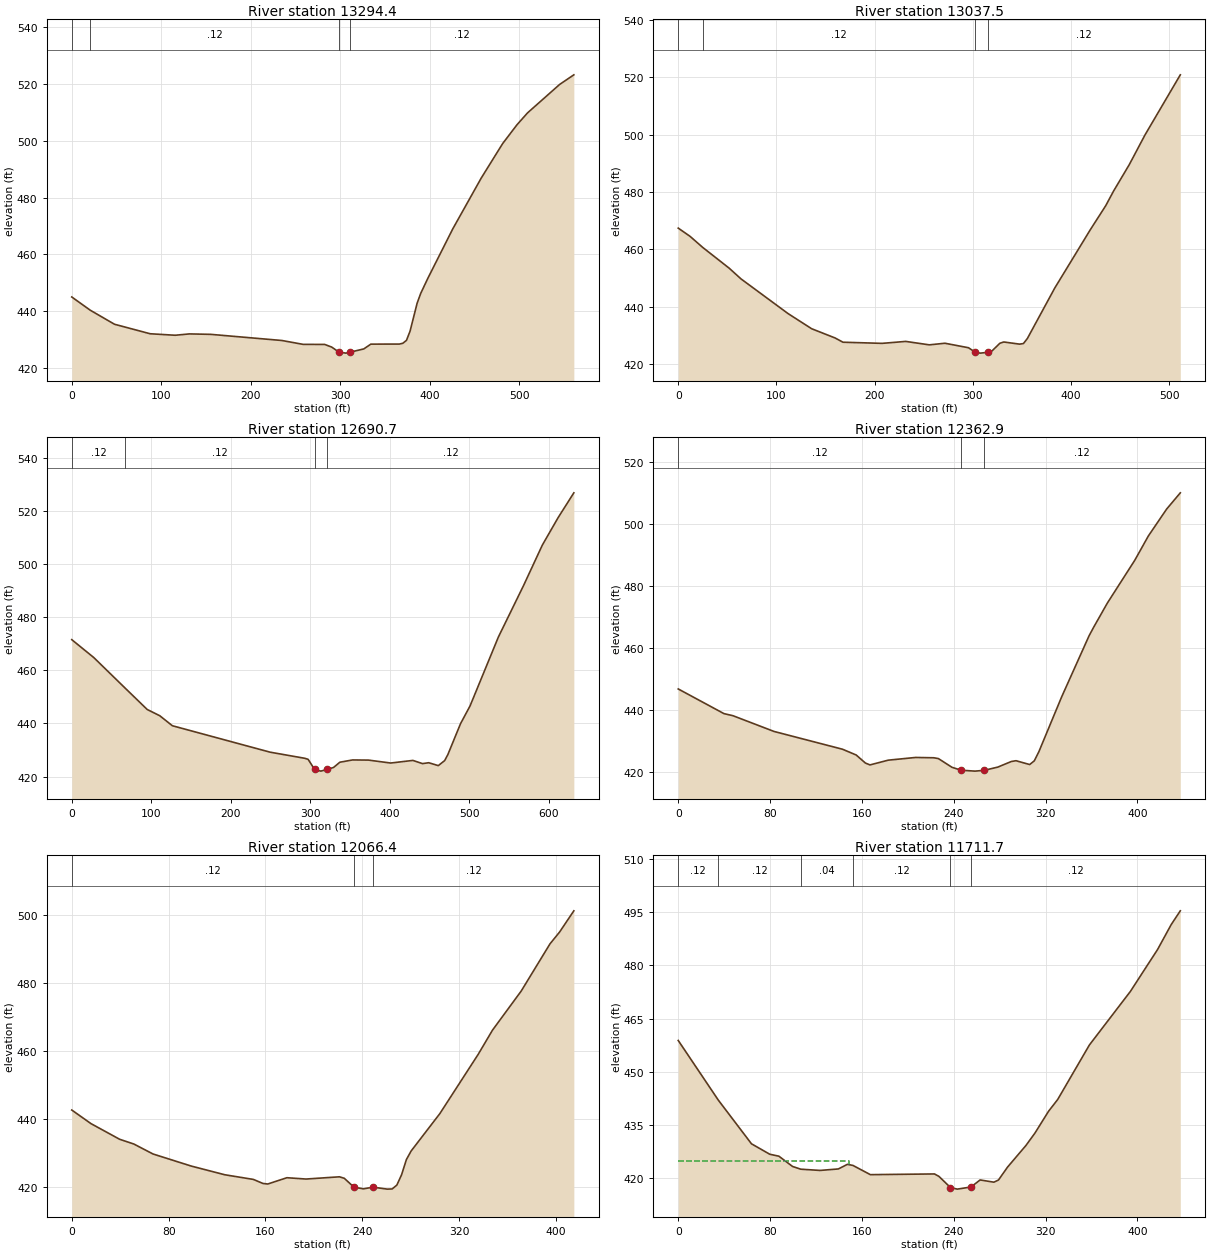
Type RM Length L Ch R = 1 ,13294.4 ,253.4,256.9,259.3
XS GIS Cut Line= 3
2377266.83109564406612.8286032532377433.49775705406601.110122755
 2377627.5081958 406258.66198875
#Sta/Elev= 30
       0     445   20.64440.3383    47.7  435.39    87.5  432.04   115.4  431.51
   131.3  431.98   155.1  431.83   234.7  429.66   258.5  428.29   282.4  428.28
   290.3  427.34   298.3  425.58   306.2  425.21   310.2   425.5   326.1  426.69
     334  428.38   365.9   428.4   369.8   428.7   373.8  429.72   377.8  432.96
   385.7  442.82   389.7  446.26   397.7  451.61   425.5     469   457.3  486.92
   481.2  499.06   497.1  505.65     509  509.88   544.8  519.89   560.7  523.29
#Mann= 4 ,-1 , 0
       0     .12       0   20.64     .12       0   298.3    .045       0
   310.2     .12       0
Bank Sta=298.3,310.2
XS Rating Curve= 0 ,0
Exp/Cntr=0.3,0.1

Type RM Length L Ch R = 1 ,13037.5 ,348.8,346.7,342.7
XS GIS Cut Line= 2
2377528.88273689406863.8992953452377830.63311763406451.370264754
#Sta/Elev= 30
       0  467.38      12  464.52   24.93460.6436    51.9  453.38    63.9  449.65
   111.8  437.54   135.8  432.25   159.7  429.02   167.7  427.54   207.6  427.14
   231.6  427.82   255.6  426.62   271.5  427.18   295.5  425.61  302.01  424.12
   307.5  423.73   315.6  424.02   319.4  424.49   327.4  427.17   331.4  427.62
   347.4  426.87   351.4  427.07   355.4  428.83   383.3  446.46   419.3  466.72
   435.2  475.23   443.2  480.34   459.2  489.58   475.2  499.95   511.1  520.91
#Mann= 4 ,-1 , 0
       0     .12       0   24.93     .12       0  302.01    .045       0
   315.6     .12       0
Bank Sta=302.01,315.6
XS Rating Curve= 0 ,0
Exp/Cntr=0.3,0.1

Type RM Length L Ch R = 1 ,12690.7 ,316.2,327.8,324.9
XS GIS Cut Line= 4
2377631.41468406406976.1100289232377851.46673739406951.370249003
2377979.07081288406702.6725836692378102.76872821406661.005672261
#Sta/Elev= 30
       0  471.55    27.7  464.81   67.42453.2262    94.9  445.26   110.7  442.91
   126.5  439.15   249.4   429.2   293.3  426.88   297.3  426.49   305.3  422.76
   313.3  422.06   321.3  422.72   329.2  423.43   337.2  425.41   353.2  426.27
   373.2  426.21   401.1  425.11   429.1  426.09   441.1  424.89     449  425.22
     461  424.13     469  426.02     473  428.26     489  439.93     501  446.63
   536.6  472.55   568.2  491.89   591.9  507.16   611.7  517.47   631.5  526.82
#Mann= 4 ,-1 , 0
       0     .12       0   67.42     .12       0   305.3    .045       0
   321.3     .12       0
Bank Sta=305.3,321.3
XS Rating Curve= 0 ,0
Exp/Cntr=0.3,0.1

Type RM Length L Ch R = 1 ,12362.9 ,272.4,296.5,317.6
XS GIS Cut Line= 2
 2377890.1021588407174.9885681722378251.74874522406929.126527086
#Sta/Elev= 30
       0  446.84    39.8   438.9    47.7  438.22    83.5  433.15   143.1  427.43
     155  425.57     163  422.99     167  422.38   182.9  423.91   206.7  424.78
   222.6  424.68   226.6  424.42   238.5   421.6   246.5  420.67   258.4  420.38
   266.4  420.63   278.3  421.67   290.2  423.49   294.2  423.73   306.1   422.5
   310.1  423.68   314.1  426.62   333.9  444.24   357.8  463.93   361.8  466.69
   373.7  474.46   397.6  488.25   409.5  496.11   425.4  504.76   437.3  509.99
#Mann= 3 ,-1 , 0
       0     .12       0   246.5    .045       0   266.4     .12       0
Bank Sta=246.5,266.4
XS Rating Curve= 0 ,0
Exp/Cntr=0.3,0.1

Type RM Length L Ch R = 1 ,12066.4 ,388,354.6,327.5
XS GIS Cut Line= 3
2377960.84151864407254.755797088 2378256.4144183407236.526502833
2378368.39385313407197.464245006
#Sta/Elev= 30
       0  442.68    15.8  438.69    39.5  434.07    51.3  432.66    67.1  429.73
    98.7  426.17   126.4  423.61     150  422.24   157.9  421.05   161.9  420.89
   177.7  422.74   193.5  422.35   221.1  423.01   225.1  422.57     233  419.98
   240.9  419.46   248.8  419.96   260.6  419.38   264.6  419.43   268.5  420.57
   272.4   423.6   276.4  428.09   280.3  430.61     304  441.61   335.7  459.08
   347.5   466.2   371.2  477.71     395  491.62   402.9  495.09   414.7  501.35
#Mann= 3 ,-1 , 0
       0     .12       0     233    .045       0   248.8     .12       0
Bank Sta=233,248.8
XS Rating Curve= 0 ,0
Exp/Cntr=0.3,0.1

Type RM Length L Ch R = 1 ,11711.7 ,294.5,274.5,249.5
XS GIS Cut Line= 3
 2378015.5290733407508.6621134282378312.40413572407448.766235843
2378433.49772555 407390.17252101
#Sta/Elev= 30
       0  458.85   34.87442.0593    63.8  429.72    79.7  426.78    87.7  426.22
    99.6  423.33  106.73422.5613   123.5  422.21   139.5  422.63   147.4  423.93
  152.22 423.619   167.4  421.02   223.2  421.22   227.1  420.54  237.16  417.39
   243.1  416.94     255  417.54     263  419.53     275   418.9     279  419.51
   286.9  423.15   302.9  429.24   310.8  432.76   322.6  438.88   330.6  442.22
   358.2  457.58   393.9  472.67   417.6   484.5   429.5  491.54   437.4   495.4
#Mann= 6 ,-1 , 0
       0     .12       0   34.87     .12       0  106.73     .04       0
  152.22     .12       0  237.16    .045       0     255     .12       0
#XS Ineff= 2 , 0
          148.61     425
Permanent Ineff=
       F       F
Bank Sta=237.16,255
XS Rating Curve= 0 ,0
Exp/Cntr=0.3,0.1

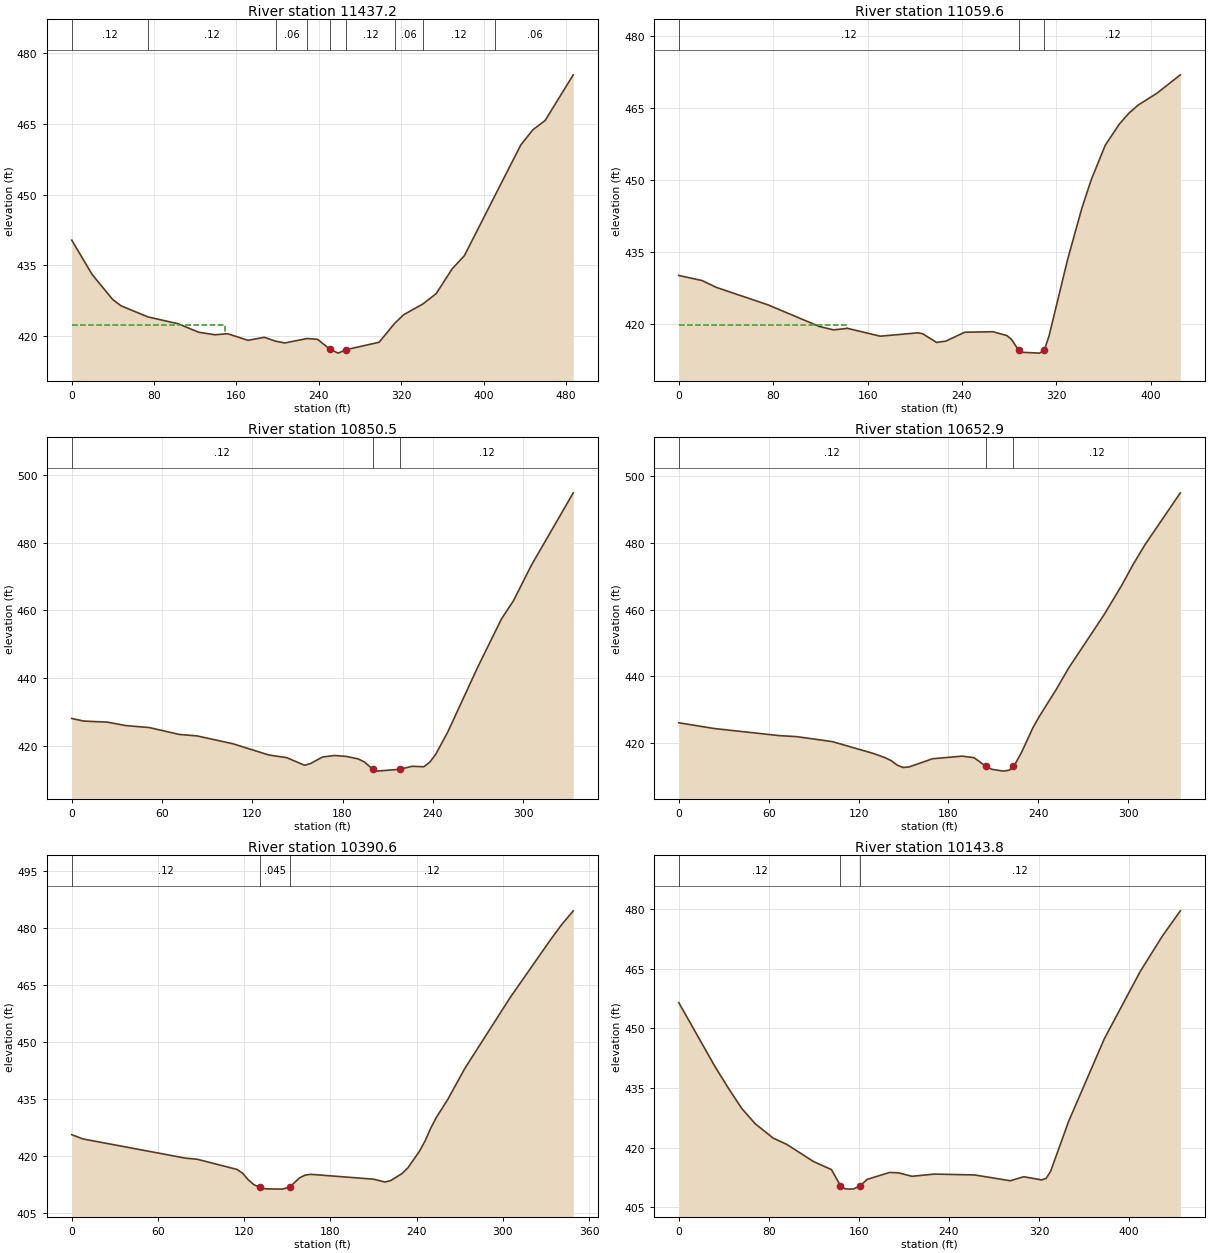
Type RM Length L Ch R = 1 ,11437.2 ,377.5,377.6,373.5
XS GIS Cut Line= 3
2378183.49789748407912.3079596762378368.39385313 407633.66219151
2378501.20625155407558.141345173
#Sta/Elev= 30
       0  440.31    19.9  432.99    39.8   427.7    47.8  426.37   74.02424.0002
   103.5  422.54   123.4  420.74   139.3  420.21   151.3  420.44   171.2  419.03
   187.1  419.67  198.02418.8455     207  418.47  228.79419.4178   238.9  419.23
   250.8  417.14   258.8  416.31   266.7  417.05   298.6  418.62  313.59422.6098
   322.5  424.48  341.02426.7324     354  428.94   369.7  434.25   381.4     437
  411.62449.9796   436.3  460.55     448  463.76   459.8   465.7   487.2  475.42
#Mann= 9 ,-1 , 0
       0     .12       0   74.02     .12       0  198.02     .06       0
  228.79     .12       0   250.8    .045       0   266.7     .12       0
  313.59     .06       0  341.02     .12       0  411.62     .06       0
#XS Ineff= 2 , 0
          148.61  422.18
Permanent Ineff=
       F       F
Bank Sta=250.8,266.7
XS Rating Curve= 0 ,0
Exp/Cntr=0.3,0.1

Type RM Length L Ch R = 1 ,11059.6 ,201.1,209.1,217
XS GIS Cut Line= 2
2378417.87275681408060.7453268472378650.94578147407705.276549593
#Sta/Elev= 30
       0   430.2    19.9  429.12    31.8  427.71    75.5  424.08   119.2  419.56
   131.1  418.86     143  419.17   170.8  417.54   202.6  418.24   206.6  418.06
   218.5  416.24   226.4  416.52   242.3  418.36   266.2  418.47   278.1  417.67
     282  416.87  287.97  414.64     290  414.19   305.9  414.01   309.9   414.7
   313.8  417.58   329.7  433.66   341.6  444.19   349.6  450.16   361.5  457.36
   373.4  461.74   381.4  463.99   389.3   465.7   405.2  468.16   425.1  472.01
#Mann= 3 ,-1 , 0
       0     .12       0  287.97    .045       0   309.9     .12       0
#XS Ineff= 2 , 0
          142.41  419.93
Permanent Ineff=
       F       F
Bank Sta=287.97,309.9
XS Rating Curve= 0 ,0
Exp/Cntr=0.3,0.1

Type RM Length L Ch R = 1 ,10850.5 ,189.6,197.6,203.5
XS GIS Cut Line= 2
2378522.03954321408097.2035872642378796.77915122407908.401471421
#Sta/Elev= 30
       0  428.14     7.9  427.38    23.8  427.06    35.7  426.06    51.6  425.46
    71.4  423.44    83.3     423   107.2  420.68     131  417.37   142.9  416.59
   154.8  414.34   158.7  414.84   166.7  416.77   174.6  417.22   182.6  416.95
   190.5   416.2   194.5  415.32  200.01  413.24   202.4  412.61   218.3  413.16
   226.2  414.04   234.1   413.9   238.1   415.3   242.1  417.67     250  424.18
   269.9   443.3   285.7  457.53   293.7  462.92   305.6  473.38   333.4  494.71
#Mann= 3 ,-1 , 0
       0     .12       0  200.01    .045       0   218.3     .12       0
Bank Sta=200.01,218.3
XS Rating Curve= 0 ,0
Exp/Cntr=0.3,0.1

Type RM Length L Ch R = 1 ,10652.9 ,251.3,262.2,269.8
XS GIS Cut Line= 3
2378576.19166589408211.9894469232378801.88412789408141.171347097
2378890.52896371    408098.50575
#Sta/Elev= 30
       0   426.1    23.6  424.38      67  422.25    78.8  421.94   102.5  420.45
   130.1  416.88     138  415.58   141.9  414.72   145.9  413.39   149.8  412.69
   153.8  412.87   169.5  415.32   189.2  416.09   197.1  415.65     205  413.07
     209  412.15   216.8   411.6   220.8   411.9  223.35  413.15   224.5  413.67
   228.7  417.08   236.5  424.65   240.5  427.84   252.3  436.29   260.2  442.44
   283.8  458.39   295.6  467.18   303.4  473.59   311.3   479.5   334.9  495.06
#Mann= 3 ,-1 , 0
       0     .12       0     205    .045       0  223.35     .12       0
Bank Sta=205,223.35
XS Rating Curve= 0 ,0
Exp/Cntr=0.3,0.1

Type RM Length L Ch R = 1 ,10390.6 ,263.8,246.9,229.2
XS GIS Cut Line= 3
2378603.53544322 408357.822816672378843.65405747408409.703618422
2378946.51868114408400.589135334
#Sta/Elev= 30
       0   425.5     7.9  424.38    79.2  419.32    87.2  419.04   114.9  416.36
   118.9  415.35   122.8  413.62   126.8  412.32   130.9  411.62   134.7  411.24
   146.6  411.16  151.75  411.75   158.5  414.14   162.4  414.86   166.4  415.06
     210  413.78   217.9  413.03   221.9  413.42   229.8  415.27   233.8  416.75
   241.7  421.02   245.7  423.76   249.6  427.11   253.6  430.04   261.6   434.8
   273.5  442.99   305.2  461.76     333  476.84     341  480.95   348.9   484.5
#Mann= 3 ,-1 , 0
       0     .12       0   130.9    .045       0  151.75     .12       0
Bank Sta=130.9,151.75
XS Rating Curve= 0 ,0
Exp/Cntr=0.3,0.1

Type RM Length L Ch R = 1 ,10143.8 ,380.9,370.9,354.4
XS GIS Cut Line= 3
 2378584.0043143408684.6459819232378693.37909555408646.885558754
2378962.91038063408456.781280175
#Sta/Elev= 30
       0   456.5    31.9  440.53    43.9  435.04    55.9  429.88    67.8  426.03
    83.8  422.41    95.8  420.84   119.7   416.5   135.6  414.48   143.5  410.47
   147.5  409.66   151.5  409.56   155.4  409.62   161.1  410.42   167.4  412.02
   187.2  413.76   195.2  413.66   207.1  412.79     227  413.35   262.7  413.13
   294.5  411.67   306.4  412.68   322.4  411.88   326.3  412.27   330.3  414.06
   346.2  426.57     378  447.43   409.8  464.32   429.6   473.3   445.5  479.62
#Mann= 3 ,-1 , 0
       0     .12       0   143.5    .045       0   161.1     .12       0
Bank Sta=143.5,161.1
XS Rating Curve= 0 ,0
Exp/Cntr=0.3,0.1

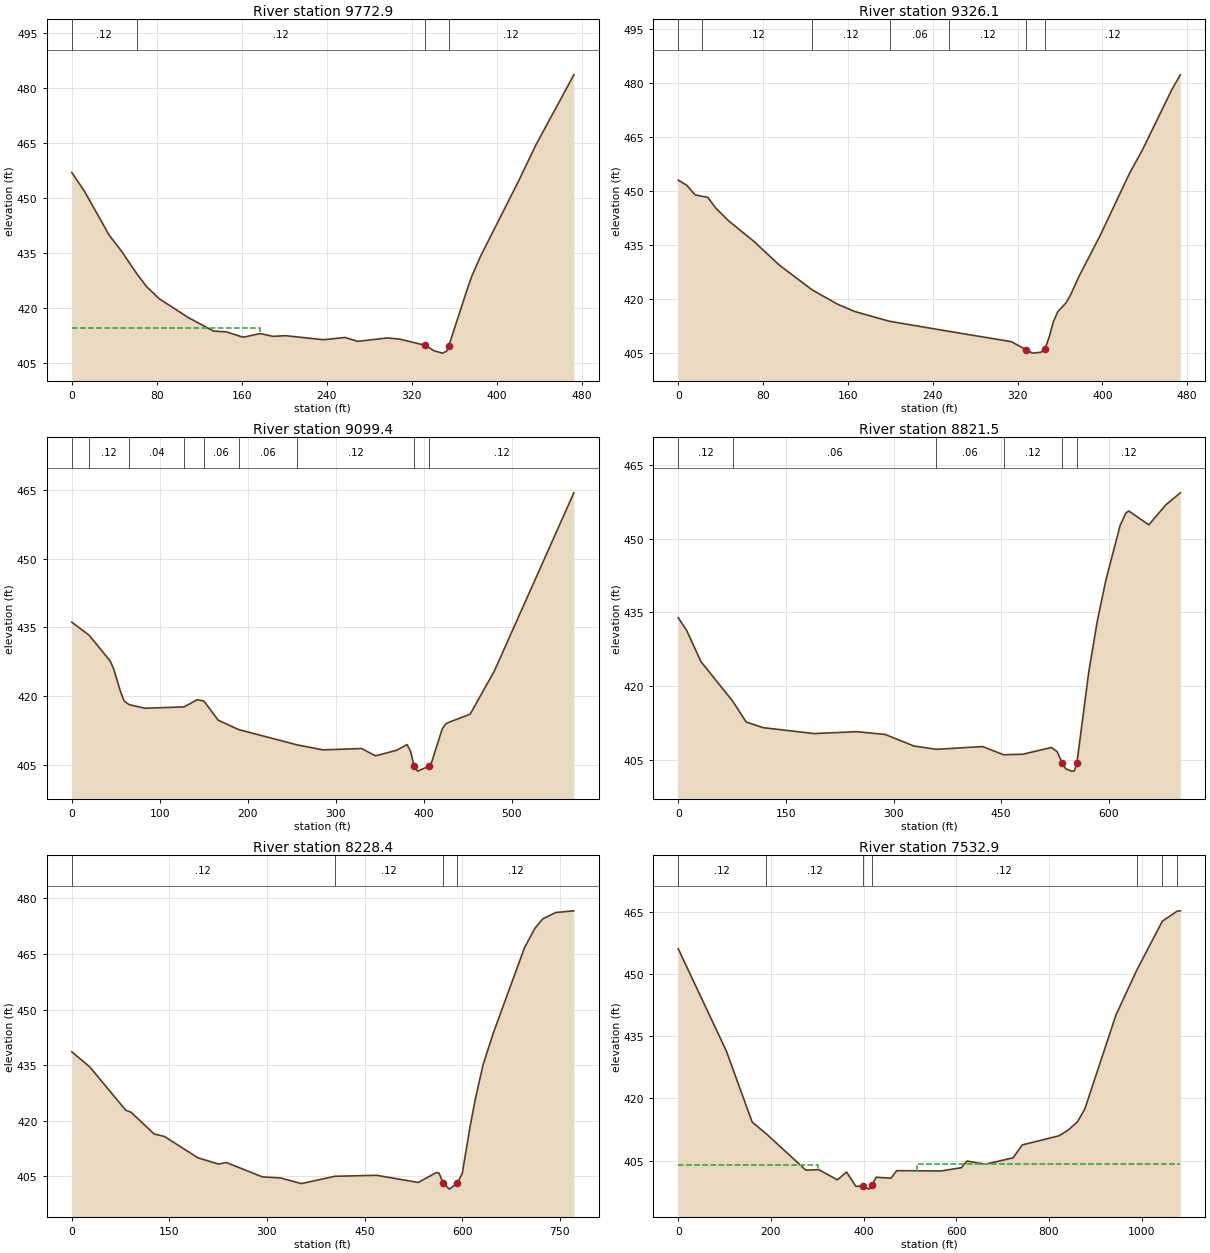
Type RM Length L Ch R = 1 ,9772.9  ,457.1,446.8,454.8
XS GIS Cut Line= 3
2378904.85209781 408957.880671682378930.89371239408843.297567502
2379092.35205089408526.891048089
#Sta/Elev= 30
       0  457.04    11.8  451.98    35.2  439.93      47  435.48   61.03429.4665
    70.5  425.85    82.2  422.58   109.7  417.42   133.5  413.72   145.4  413.51
   161.4  412.04   177.4  413.05   189.4  412.29   201.3  412.46   237.2  411.36
   257.2  411.98   269.2  410.92   297.1  411.85   309.1   411.5     333  409.82
     341  408.35     349   407.7     353  408.24  355.03  409.75   372.9  425.66
   376.9  428.91   384.9  434.18   420.8  454.77   436.8  464.46   472.7   483.7
#Mann= 4 ,-1 , 0
       0     .12       0   61.03     .12       0     333    .045       0
  355.03     .12       0
#XS Ineff= 2 , 0
           177.5  414.53
Permanent Ineff=
       F       F
Bank Sta=333,355.03
XS Rating Curve= 0 ,0
Exp/Cntr=0.3,0.1

Type RM Length L Ch R = 1 ,9326.1  ,231.1,226.7,220
XS GIS Cut Line= 3
2379360.58117321409020.3808747532379331.93523313408815.953790173
 2379341.0500443408549.026502505
#Sta/Elev= 30
       0  452.97     7.9  451.57    15.9  448.88   22.04448.5016    27.8  448.19
    35.7  445.12    47.6  441.64    71.4  435.96    95.3   429.4  126.35 422.515
   150.8  418.47   166.7   416.5  199.29413.8055  255.54411.0091     314  408.17
     328  405.96     334  404.98     342  405.22     346  406.21   349.9  409.53
   353.9  413.78   357.9  416.45   365.9  418.98   369.9  421.07   377.8  426.19
   397.8  437.53   425.7   454.9   437.6  461.23   465.5  478.05   473.5  482.16
#Mann= 7 ,-1 , 0
       0    .016       0   22.04     .12       0  126.35     .12       0
  199.29     .06       0  255.54     .12       0     328    .045       0
     346     .12       0
Bank Sta=328,346
XS Rating Curve= 0 ,0
Exp/Cntr=0.3,0.1

Type RM Length L Ch R = 1 ,9099.4  ,272.4,278,283.1
XS GIS Cut Line= 4
2379506.41454297409015.172551841 2379598.8625208 408862.82869643
2379541.57064064408594.5995740892379430.89369664408554.234825417
#Sta/Elev= 30
       0  436.14   19.73433.3029    43.6  427.68    47.5  426.01    55.4  420.98
    59.4  418.97   64.89418.1521    83.2  417.35  127.44  417.65   142.6  419.22
   150.1 418.923   166.3  414.75  189.52412.6972  256.31 409.336   285.5  408.26
   329.2  408.55   345.2  406.95     369  408.18   380.9  409.41   384.9   407.9
   388.9  404.67   392.8  403.62  406.11  404.73   408.8  405.57   420.7  412.79
   424.6  413.88   428.6   414.3   452.5  416.05     480  425.48   570.3  464.39
#Mann= 9 ,-1 , 0
       0     .06       0   19.73     .12       0   64.89     .04       0
  127.44     .12       0   150.1     .06       0  189.52     .06       0
  256.31     .12       0   388.9    .045       0  406.11     .12       0
Bank Sta=388.9,406.11
XS Rating Curve= 0 ,0
Exp/Cntr=0.3,0.1

Type RM Length L Ch R = 1 ,8821.5  ,577.9,593.1,606.8
XS GIS Cut Line= 3
2379770.73750514409141.4744645952379815.00841397408888.870311007
2379823.37060197408445.749806181
#Sta/Elev= 30
       0  433.94    11.8  431.33    31.6  424.99    75.7416.9585    94.7  412.66
   118.4  411.51   189.4  410.31   248.6  410.69   288.4  410.13   328.3  407.78
  359.65 407.096   424.2  407.66  453.29405.9902     480  406.09     520  407.47
     528  406.61  535.08   404.3   539.9  403.14   547.9  402.65   551.9  402.69
   555.5  404.28   571.9  422.72   583.9  433.21   595.8  441.55   615.8  452.77
   623.8   455.3   627.8   455.7   655.7  452.88   679.7  456.98   699.6   459.4
#Mann= 6 ,-1 , 0
       0     .12       0    75.7     .06       0  359.65     .06       0
  453.29     .12       0  535.08    .045       0   555.5     .12       0
Bank Sta=535.08,555.5
XS Rating Curve= 0 ,0
Exp/Cntr=0.3,0.1

Type RM Length L Ch R = 1 ,8228.4  ,677.3,695.5,712.1
XS GIS Cut Line= 3
2380057.19592172409305.5371285982380153.55005972409084.182912514
2380476.46673672408663.609934762
#Sta/Elev= 30
       0  438.62    27.7  434.53    83.1  422.82      91  422.32   126.6  416.44
   142.5  415.76   193.9     410   225.6  408.31   237.5  408.74   293.2  404.84
   321.2  404.56     353  403.05  404.45405.0199   468.7  405.28   532.4  403.35
   560.4  406.02   564.4  405.88  571.18  403.11   580.3  401.55   592.2  403.09
   600.2  405.77   612.2  418.42   620.2  425.78   632.1  435.06   648.1  443.77
   695.9  466.72   711.9  471.94   723.8  474.48   743.8   476.2   771.7  476.66
#Mann= 4 ,-1 , 0
       0     .12       0  404.45     .12       0  571.18    .045       0
   592.2     .12       0
Bank Sta=571.18,592.2
XS Rating Curve= 0 ,0
Exp/Cntr=0.3,0.1

Type RM Length L Ch R = 1 ,7532.9  ,493.2,483.2,470.6
XS GIS Cut Line= 4
 2380372.2999503409547.7246363462380421.77918205   409341.995389
 2380873.6020973409258.6618942622380929.59148663408849.807725087
#Sta/Elev= 30
       0   456.1   103.8  431.45   159.7  414.28  189.69411.4994   275.5   402.7
   303.5  402.82   343.4  400.36   363.4  402.23   383.4  398.79   399.4   398.9
   411.4  398.12   417.9  399.04   427.3     401   459.3  400.75   471.3  402.57
   567.2   402.5   611.1  403.29   623.1  404.89     663  404.13   722.6  405.67
   742.5  408.78   821.8  410.99   841.7  412.36   861.5  414.34   877.4   417.4
   944.8  440.12  989.85450.9723 1044.94462.7522 1076.88465.1705  1083.7  465.25
#Mann= 7 ,-1 , 0
       0     .12       0  189.69     .12       0   399.4    .045       0
   417.9     .12       0  989.85     .06       0 1044.94     .12       0
 1076.88     .06       0
#XS Ineff= 2 , 0
          300.93  403.92  516.41          404.19
Permanent Ineff=
       F       F
Bank Sta=399.4,417.9
XS Rating Curve= 0 ,0
Exp/Cntr=0.3,0.1

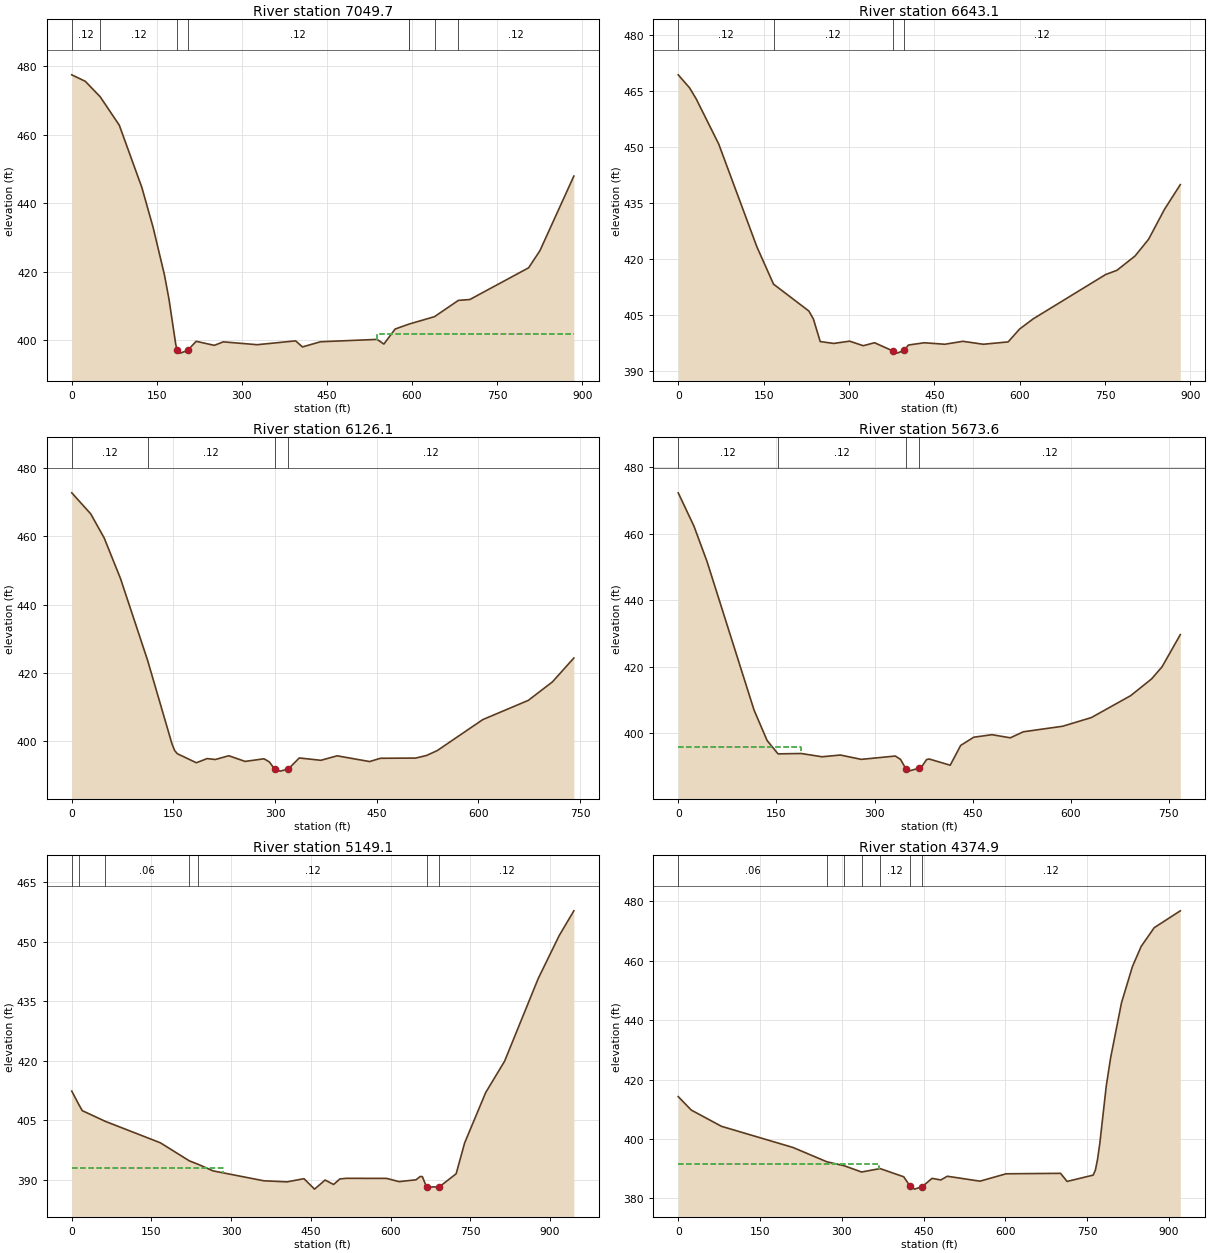
Type RM Length L Ch R = 1 ,7049.7  ,395.6,406.6,413.6
XS GIS Cut Line= 2
2380597.96550947409827.2962556782381307.60090122409297.782550916
#Sta/Elev= 30
       0  477.54    23.9  475.64   50.09471.1376    83.8  462.84   123.6  444.66
   143.6  432.91   163.5  419.09   171.5     412   183.5  398.72   186.3  397.09
   191.4  396.29   204.2  397.07   219.4  399.74   251.3  398.56   267.2  399.58
     327  398.75   394.8  399.87   406.8   398.1   438.7  399.61   538.4   400.3
   550.4  398.94   570.3  403.33  594.89404.7762  595.01404.7795  639.71406.9387
  681.81  411.69     702  411.94   805.6   421.2   825.6   426.2   885.4  447.98
#Mann= 8 ,-1 , 0
       0     .12       0   50.09     .12       0   186.3    .045       0
   204.2     .12       0  594.89     .06       0  595.01    .016       0
  639.71     .08       0  681.81     .12       0
#XS Ineff= 2 , 0
                           538.7          401.79
Permanent Ineff=
       F       F
Bank Sta=186.3,204.2
XS Rating Curve= 0 ,0
Exp/Cntr=0.3,0.1

Type RM Length L Ch R = 1 ,6643.1  ,508.9,517,529.2
XS GIS Cut Line= 3
2380771.57671081410113.7546722592380884.42392606409966.185085505
 2381544.1460318409742.660926253
#Sta/Elev= 30
       0  469.24    19.8  465.79    31.6  462.81    71.2  450.74   138.3  423.26
  167.49413.3246   229.6  406.14   237.5  404.02   249.5  397.99   273.3  397.49
   301.2   398.1   325.1  396.88     345  397.68   376.8   395.5   384.8   394.9
   396.7  395.64   404.7  397.07   432.6  397.67   468.4  397.27   500.2  398.06
     536  397.27   579.8   397.9   599.7  401.31   623.6  404.04     751  415.89
   770.9  417.02   802.7  420.84   826.6  425.32   854.5  433.32   882.3  439.91
#Mann= 4 ,-1 , 0
       0     .12       0  167.49     .12       0   376.8    .045       0
   396.7     .12       0
Bank Sta=376.8,396.7
XS Rating Curve= 0 ,0
Exp/Cntr=0.3,0.1

Type RM Length L Ch R = 1 ,6126.1  ,451.9,452.6,451.5
XS GIS Cut Line= 3
2380783.36868197410234.7481966762381309.45457205410333.585925505
2381514.55882064 410344.32376492
#Sta/Elev= 30
       0  472.74      28  466.58    47.9   459.5    71.9  447.66  111.83423.7615
   147.8  399.32   151.8  397.33   155.8   396.4   183.8  393.76   199.7  394.98
   211.7  394.71   231.7  395.81   255.7  394.15   283.6  394.92   291.6  393.99
   299.6  391.81   307.6  391.31   319.6  391.96   335.6  395.16   367.5  394.48
   391.5  395.79   439.4  394.11   455.4  395.07   507.3  395.13   523.3  395.88
   539.2  397.32   606.4  406.39   673.5  412.01   709.1  417.42   740.7  424.41
#Mann= 4 ,-1 , 0
       0     .12       0  111.83     .12       0   299.6    .045       0
   319.6     .12       0
Bank Sta=299.6,319.6
XS Rating Curve= 0 ,0
Exp/Cntr=0.3,0.1

Type RM Length L Ch R = 1 ,5673.6  ,544.7,524.4,501.8
XS GIS Cut Line= 2
2380684.77111013410589.0152046682381431.29881655410766.966292337
#Sta/Elev= 30
       0  472.37      24  462.36      44  451.72   115.9  407.02   135.9  397.85
  152.55393.8508   187.9  393.96   219.8  392.98   247.8   393.5   279.8   392.2
   331.8   393.2   339.8  392.19   347.8  389.42   351.8  388.66   367.7  389.53
   371.7  389.86   379.7  392.16   383.7   392.3   415.7  390.44   431.7  396.39
   451.7  398.86   479.6  399.62   507.6  398.68   527.6   400.5   587.6  402.16
   631.5  404.77   691.5  411.36   723.5   416.4   739.5  420.04   767.4  429.72
#Mann= 4 ,-1 , 0
       0     .12       0  152.55     .12       0   347.8    .045       0
   367.7     .12       0
#XS Ineff= 2 , 0
          187.41  395.88
Permanent Ineff=
       F       F
Bank Sta=347.8,367.7
XS Rating Curve= 0 ,0
Exp/Cntr=0.3,0.1

Type RM Length L Ch R = 1 ,5149.1  ,795.6,774.3,751.9
XS GIS Cut Line= 4
2380778.08686839411628.5114852642380875.74316913411385.455869004
2381264.19810088411068.6156234292381444.31978789411092.487294838
#Sta/Elev= 30
       0  412.31    13.8408.7993    19.8  407.39   63.01404.6998   166.7  399.29
  221.26394.7375  238.22393.8416   265.9  392.21   361.4  389.71   405.2  389.44
     437  390.24   456.9  387.61   476.8   389.9   492.7  388.78   504.6  390.18
   516.6  390.33   592.2  390.32     616   389.5   647.8  389.96   655.8   390.8
   659.8  390.76   667.7  388.15   691.6  388.17   723.4  391.48   739.4  399.26
     779  411.95   814.6  419.86   877.8  440.67   917.3   451.5   944.9  457.75
#Mann= 7 ,-1 , 0
       0     .12       0    13.8    .016       0   63.01     .06       0
  221.26     .06       0  238.22     .12       0   667.7    .045       0
   691.6     .12       0
#XS Ineff= 2 , 0
           283.8  392.84
Permanent Ineff=
       F       F
Bank Sta=667.7,691.6
XS Rating Curve= 0 ,0
Exp/Cntr=0.3,0.1

Type RM Length L Ch R = 1 ,4374.9  ,400.2,393.3,384.3
XS GIS Cut Line= 3
2381422.61838771412010.4559313362381574.52786081411782.591557667
2381550.65651748411135.890095174
#Sta/Elev= 30
       0  414.26    23.8  409.74    79.4  404.25   210.4  397.14  272.61392.3177
  304.73390.9668  336.32388.8744  370.35390.0251   413.7  387.26   425.7     384
   433.6  383.11  447.83  383.98   465.6  386.74   481.6  386.19   493.6  387.45
   553.5  385.79   601.4  388.27   701.3  388.43   713.3   385.7   761.2  387.83
   765.2   389.5   769.2  393.14   773.2  398.32   785.2  417.89   793.2  427.35
   813.1  445.84   833.1  458.02   849.1  464.79   873.1  471.13     921  476.81
#Mann= 7 ,-1 , 0
       0     .06       0  272.61     .06       0  304.73     .04       0
  336.32     .06       0  370.35     .12       0   425.7    .045       0
  447.83     .12       0
#XS Ineff= 2 , 0
          367.39  391.49
Permanent Ineff=
       F       F
Bank Sta=425.7,447.83
XS Rating Curve= 0 ,0
Exp/Cntr=0.3,0.1

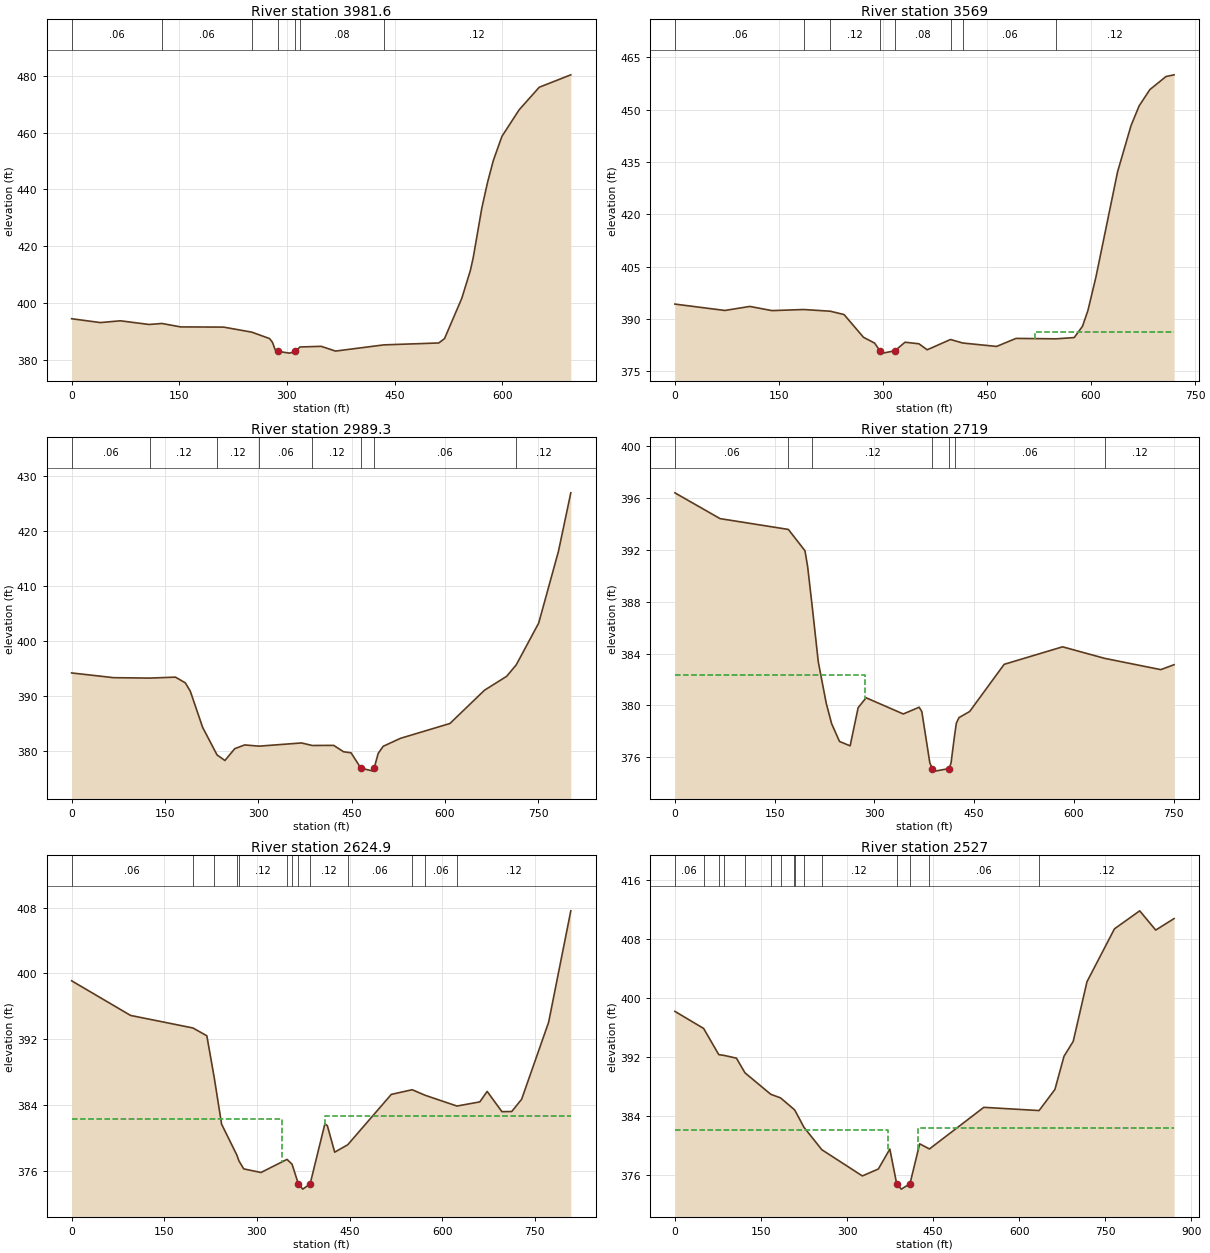
Type RM Length L Ch R = 1 ,3981.6  ,405.3,412.5,417.6
XS GIS Cut Line= 3
2382047.61812197411778.2510151712381837.11460596411272.608653754
2381826.26390588411125.039395094
#Sta/Elev= 30
       0  394.38      40  393.03      68  393.65   107.9  392.36  125.88392.7098
   151.9   391.5   211.9  391.43  251.06389.6546   275.8   387.4   279.8  386.12
   283.8  383.41   287.8  382.86   303.8  382.26   311.8  382.89  318.33384.4254
   347.8  384.66   367.8  382.98  435.14385.1685   511.7  385.84   519.7  387.37
   543.7  401.53   555.7  411.36   559.7  415.92   571.7   433.4   579.7  442.48
   587.7  450.13   599.7  458.65   623.7  468.01   651.7  475.96   695.7  480.34
#Mann= 7 ,-1 , 0
       0     .06       0  125.88     .06       0  251.06     .12       0
   287.8    .045       0   311.8     .12       0  318.33     .08       0
  435.14     .12       0
Bank Sta=287.8,311.8
XS Rating Curve= 0 ,0
Exp/Cntr=0.3,0.1

Type RM Length L Ch R = 1 ,3569    ,559.2,579.7,593.7
XS GIS Cut Line= 3
2382357.94820997411704.4663858412382273.31255247411122.869123846
2382212.54889447 411005.68169418
#Sta/Elev= 30
       0  394.24      72  392.41     108  393.57   139.9  392.37  185.73392.6822
  223.94392.1988   243.9  391.24   271.9  384.72   287.9  383.06   295.9  380.79
   299.9  380.18  317.38  380.87   331.8  383.31   351.8  382.86   363.8  381.14
  397.36384.0858  415.11383.0766   463.8   382.1   491.8   384.4  549.66384.2796
   575.7  384.64   587.7  387.89   595.5  392.42   607.1  402.06   638.2  432.15
   657.6  445.39   669.3  451.06   684.8  455.74   708.1  459.49   719.7  459.97
#Mann= 8 ,-1 , 0
       0     .06       0  185.73     .06       0  223.94     .12       0
   295.9    .045       0  317.38     .08       0  397.36     .12       0
  415.11     .06       0  549.66     .12       0
#XS Ineff= 2 , 0
                          518.47          386.22
Permanent Ineff=
       F       F
Bank Sta=295.9,317.38
XS Rating Curve= 0 ,0
Exp/Cntr=0.3,0.1

Type RM Length L Ch R = 1 ,2989.3  ,264.2,270.3,270.5
XS GIS Cut Line= 3
2382577.13215481411682.7649856812382863.59057139411155.421224087
2382876.61121464410953.598465011
#Sta/Elev= 30
       0   394.2    67.6  393.34   126.2 393.265   166.9  393.44   182.8   392.4
   190.8  390.88   210.6  384.33  233.77379.3286   246.4  378.32   262.3  380.47
   278.2  381.14  301.34380.9202   369.6   381.5   386.7 381.043   421.3  381.06
   437.2   379.9   449.1  379.72     465  376.93   484.9  376.39   486.2  376.89
   492.8  379.61   500.8  380.89   528.6  382.34   608.1  385.03   663.6  391.06
   699.3  393.59  714.71 395.667   750.8  403.25   782.5  416.24   802.4  426.87
#Mann= 8 ,-1 , 0
       0     .06       0   126.2     .12       0  233.77     .12       0
  301.34     .06       0   386.7     .12       0     465    .045       0
   486.2     .06       0  714.71     .12       0
Bank Sta=465,486.2
XS Rating Curve= 0 ,0
Exp/Cntr=0.3,0.1

Type RM Length L Ch R = 1 ,2719    ,92,94.1,95
XS GIS Cut Line= 2
2382676.20610364411745.3806740942383175.95477605411185.355547428
#Sta/Elev= 30
       0   396.4    67.9  394.41  170.62393.5765   195.6  391.93   199.6  390.71
  206.74387.5078   215.6  383.36   227.6  380.16   235.6   378.6   247.5  377.22
   263.5  376.88   275.5  379.82   287.5  380.59   343.4  379.34   367.3  379.86
   371.3  379.52   383.3  375.58   387.3   375.1   391.3  374.93  412.38  375.13
   415.2  375.55  420.74377.7628   423.2  378.63   427.2  379.06   443.2  379.53
   495.1  383.17   582.9  384.52  646.36383.6278   730.6  382.76   750.6  383.14
#Mann= 7 ,-1 , 0
       0     .06       0  170.62     .12       0  206.74     .12       0
   387.3    .045       0  412.38     .12       0  420.74     .06       0
  646.36     .12       0
#XS Ineff= 2 , 0
          286.48  382.36
Permanent Ineff=
       F       F
Bank Sta=387.3,412.38
XS Rating Curve= 0 ,0
Exp/Cntr=0.3,0.1

Type RM Length L Ch R = 1 ,2624.9  ,97.5,97.9,97.3
XS GIS Cut Line= 2
2382719.17484972411784.4432600142383298.26686738411220.841368839
#Sta/Elev= 30
       0  399.11    95.5   394.9   196.3  393.38   218.9  392.43  230.66387.4408
   242.8  381.69  267.65377.9157  270.78 377.244   278.6  376.26   306.5  375.82
  348.72377.4156   356.9376.8225  367.06  374.43   374.2   373.8   386.1  374.43
     410  381.73     414  381.51   425.9  378.29  446.94379.1855   517.5  385.31
  551.37385.8741  572.21385.2047   623.8 383.893   660.8   384.4   672.7  385.67
   696.6  383.21   712.5  383.23   728.5  384.72   772.2  394.07   808.1  407.61
#Mann= 13 ,-1 , 0
       0     .06       0   196.3     .06       0  230.66     .12       0
  267.65    .016       0  270.78     .12       0  348.72     .06       0
   356.9     .12       0  367.06    .045       0   386.1     .12       0
  446.94     .06       0  551.37     .12       0  572.21     .06       0
   623.8     .12       0
#XS Ineff= 2 , 0
          340.56  382.36   409.7          382.64
Permanent Ineff=
       F       F
Bank Sta=367.06,386.1
XS Rating Curve= 0 ,0
Exp/Cntr=0.3,0.1

Type RM Length L Ch R = 1 ,2527    ,201.6,185.8,168.4
XS GIS Cut Line= 3
2382743.91462964411796.1620685912382892.35199681411751.891159758
2383402.92741922411251.205809429
#Sta/Elev= 30
       0  398.18   50.05395.8636   76.49392.3119   84.97392.2208   107.2  391.84
  122.12389.8484  167.05386.9381  184.12386.4512   208.3  384.85  209.94384.6532
   224.8  382.48  256.08379.4236   326.7  375.87   354.6  376.81   374.6  379.51
   386.6  374.78   394.6  374.08  409.74  374.82   426.6  380.22  443.65379.5256
   538.4  385.17  634.71384.7305   662.3  387.59   678.2   392.1   694.2  394.11
   718.2   402.2   766.1  409.37   810.1  411.81     838   409.2     870  410.76
#Mann= 15 ,-1 , 0
       0     .06       0   50.05    .016       0   76.49     .12       0
   84.97    .016       0  122.12     .06       0  167.05     .12       0
  184.12     .06       0   208.3     .06       0  209.94     .12       0
   224.8     .06       0  256.08     .12       0   386.6    .045       0
  409.74     .12       0  443.65     .06       0  634.71     .12       0
#XS Ineff= 2 , 0
          371.52  382.16  424.15          382.42
Permanent Ineff=
       F       F
Bank Sta=386.6,409.74
XS Rating Curve= 0 ,0
Exp/Cntr=0.3,0.1

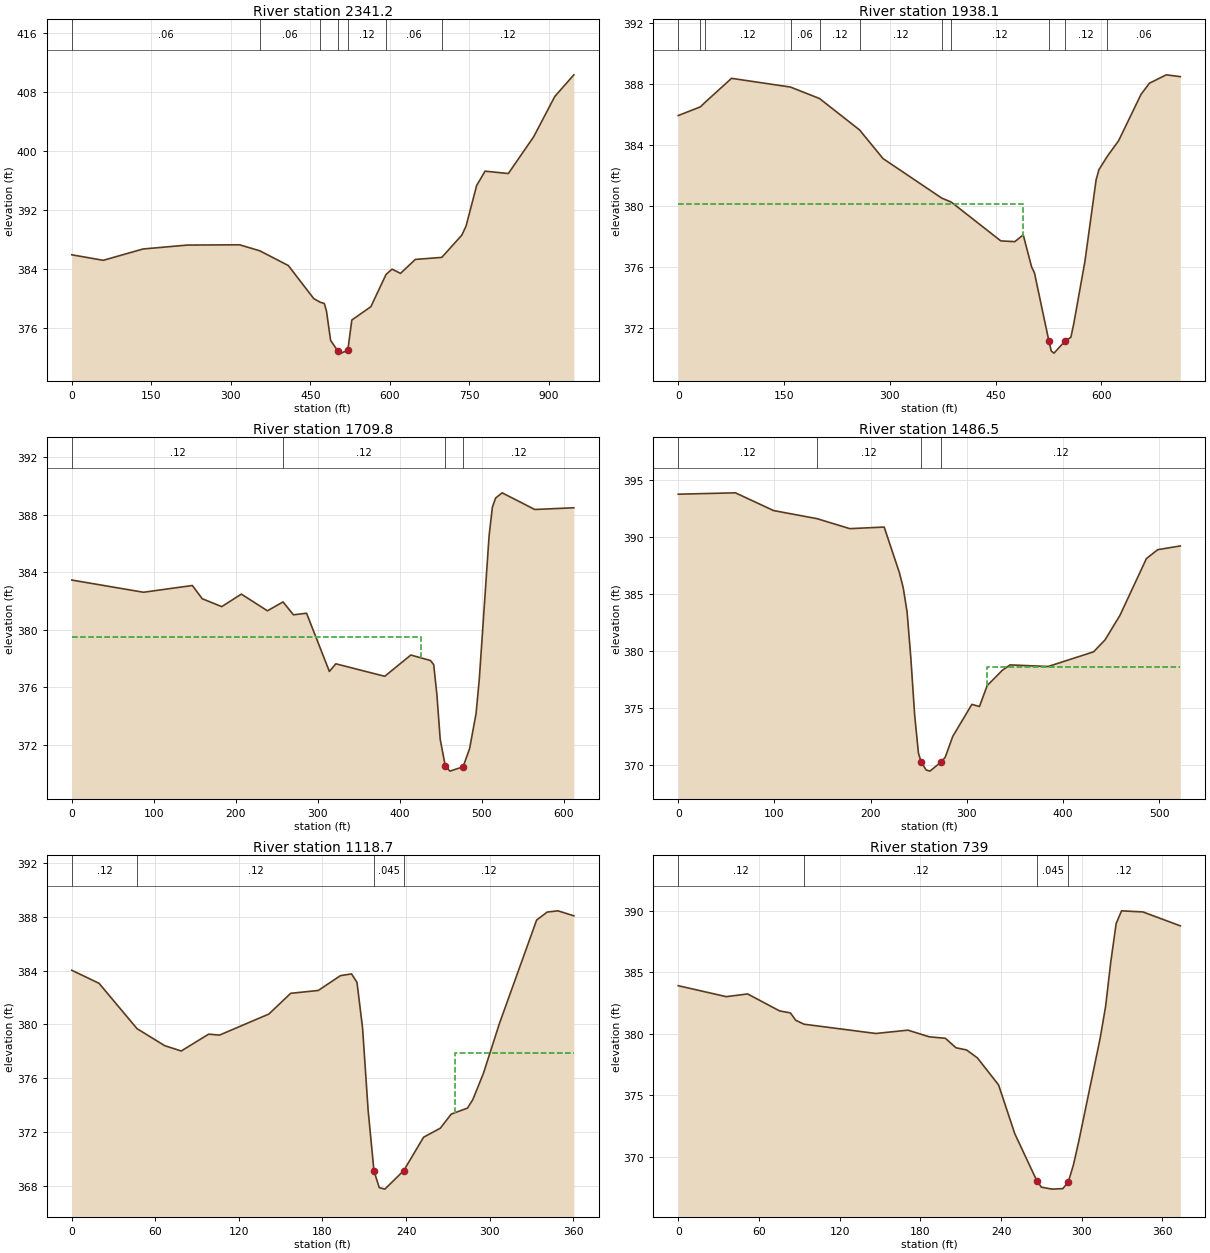
Type RM Length L Ch R = 1 ,2341.2  ,386.2,403.1,448.6
XS GIS Cut Line= 4
2382896.25815697411818.2975230072383200.94586781411823.505845919
 2383232.1958053411465.4327431772383424.30598539411257.408224836
#Sta/Elev= 30
       0  385.91    59.4  385.16   134.6   386.7   217.7  387.23   316.7  387.27
  354.64386.4552   408.6  384.45   456.5  379.96  468.66379.4676   476.5  379.28
   480.5   378.3   488.4  374.27   501.6  372.87   508.4  372.54  520.83  372.95
   528.4  377.04   564.3  378.85  593.04383.2473   604.3  383.96   620.2  383.38
   648.2  385.28  698.18385.5584     736  388.59   743.9  389.81   763.9  395.33
   779.8  397.28   823.7  396.96   871.6  401.97   911.4  407.44   947.3  410.38
#Mann= 7 ,-1 , 0
       0     .06       0  354.64     .06       0  468.66     .12       0
   501.6    .045       0  520.83     .12       0  593.04     .06       0
  698.18     .12       0
Bank Sta=501.6,520.83
XS Rating Curve= 0 ,0
Exp/Cntr=0.3,0.1

Type RM Length L Ch R = 1 ,1938.1  ,220.1,228.3,199.3
XS GIS Cut Line= 2
2383187.97804597411883.0099920032383700.58824122411388.781649753
#Sta/Elev= 30
       0  385.95   31.38 386.519   38.64386.8407    75.6  388.39  159.24387.8172
  200.44387.0654  257.18385.0068   290.4  383.13   373.7380.5372  387.23380.2761
   457.5  377.73   477.4  377.68   489.3  378.13   501.2  376.02   505.2  375.64
  525.74  371.16   529.1   370.5     533  370.37     549  371.18   556.9  371.41
   560.9  372.28   576.8  376.38   592.7  381.74   596.7   382.4  608.63383.2819
   624.6   384.3   656.4  387.34   668.3  388.07   692.2  388.62   712.1   388.5
#Mann= 11 ,-1 , 0
       0     .12       0   31.38     .06       0   38.64     .12       0
  159.24     .06       0  200.44     .12       0  257.18     .12       0
   373.7     .06       0  387.23     .12       0  525.74    .045       0
     549     .12       0  608.63     .06       0
#XS Ineff= 2 , 0
          489.58  380.14
Permanent Ineff=
       F       F
Bank Sta=525.74,549
XS Rating Curve= 0 ,0
Exp/Cntr=0.3,0.1

Type RM Length L Ch R = 1 ,1709.8  ,237.2,223.3,208.2
XS GIS Cut Line= 2
2383402.82177639411948.1141925012383842.87273355411522.724623337
#Sta/Elev= 30
       0  383.45    87.4   382.6     147  383.07     159  382.15   182.8   381.6
   206.7  382.47   238.5  381.31  257.53381.9262   270.2  381.03   286.2  381.14
     314  377.09   321.9  377.62   381.5  376.75   413.3  378.23   437.2  377.85
   441.2  377.56   445.1  375.45   449.1  372.37  455.31   370.5     461  370.15
     477  370.45   484.9  371.71   492.8  374.15   496.8  376.59   508.7  386.53
   512.7  388.52   516.7  389.16   524.6  389.52   564.4  388.36     612  388.48
#Mann= 4 ,-1 , 0
       0     .12       0  257.53     .12       0  455.31    .045       0
     477     .12       0
#XS Ineff= 2 , 0
          426.21  379.46
Permanent Ineff=
       F       F
Bank Sta=455.31,477
XS Rating Curve= 0 ,0
Exp/Cntr=0.3,0.1

Type RM Length L Ch R = 1 ,1486.5  ,408.3,367.8,326.4
XS GIS Cut Line= 3
 2383811.8304728412052.0742864162383883.23748222411654.234859005
2383863.70635331 411538.34959209
#Sta/Elev= 30
       0  393.79    59.4  393.91    99.1  392.35  144.17391.6389   178.3  390.76
     214   390.9   229.8  386.89   233.8  385.55   237.8  383.44   241.7  379.38
   245.7  374.34   249.6  371.02   252.5  370.24   257.6  369.54   261.5  369.44
   273.4  370.26   277.4  370.66   285.3   372.5   305.1  375.31     313  375.12
     321  376.96   336.8  378.31   344.8  378.78   384.4  378.64   431.6  379.93
   443.4  380.97     459  383.14   486.5  388.13   498.2  388.91   521.7  389.24
#Mann= 4 ,-1 , 0
       0     .12       0  144.17     .12       0   252.5    .045       0
   273.4     .12       0
#XS Ineff= 2 , 0
                          320.74          378.63
Permanent Ineff=
       F       F
Bank Sta=252.5,273.4
XS Rating Curve= 0 ,0
Exp/Cntr=0.3,0.1

Type RM Length L Ch R = 1 ,1118.7  ,342.5,379.7,416.6
XS GIS Cut Line= 4
2384291.25241421411627.1732333452384146.81536713411539.369603172
2384039.48749781411544.8600777542383975.68546005411490.172523096
#Sta/Elev= 30
       0  384.02    19.6  383.05   46.86379.6872    66.8  378.42    78.6  378.03
    98.3  379.28   106.1  379.21   141.5  380.77   157.2  382.31     177  382.52
   192.9  383.62   200.9  383.75   204.8  383.12   208.8  379.74   212.8  373.62
     217  369.12   220.8  367.89   224.8  367.78  238.33  369.15   252.6  371.63
   264.6   372.3   272.5  373.35   284.1  373.79     288  374.43   295.6  376.38
   307.1  380.08   333.8  387.75   341.4  388.34   349.1  388.43   360.5  388.06
#Mann= 4 ,-1 , 0
       0     .12       0   46.86     .12       0     217    .045       0
  238.33     .12       0
#XS Ineff= 2 , 0
                          275.34          377.88
Permanent Ineff=
       F       F
Bank Sta=217,238.33
XS Rating Curve= 0 ,0
Exp/Cntr=0.3,0.1

Type RM Length L Ch R = 1 ,739     ,243.2,232.1,221
XS GIS Cut Line= 2
2384315.55813989411587.9370913362384315.55813989411214.673402175
#Sta/Elev= 30
       0  383.91    35.7  383.02    51.6  383.24    75.4  381.86    83.4   381.7
    87.4   381.1   93.51380.7827   146.9  380.03   170.8   380.3   186.6  379.76
   198.6  379.64   206.5  378.87   214.4  378.69   222.4  378.05   238.2  375.85
   250.2   371.9   266.7  368.05     270  367.55     278  367.39   285.9  367.43
   289.9  367.94   293.8  369.34   297.8  371.27   313.7  379.64   317.7  382.19
   321.6  385.83   325.6  388.96   329.6  389.99   345.5   389.9   373.3  388.77
#Mann= 4 ,-1 , 0
       0     .12       0   93.51     .12       0   266.7    .045       0
   289.9     .12       0
Bank Sta=266.7,289.9
XS Rating Curve= 0 ,0
Exp/Cntr=0.3,0.1