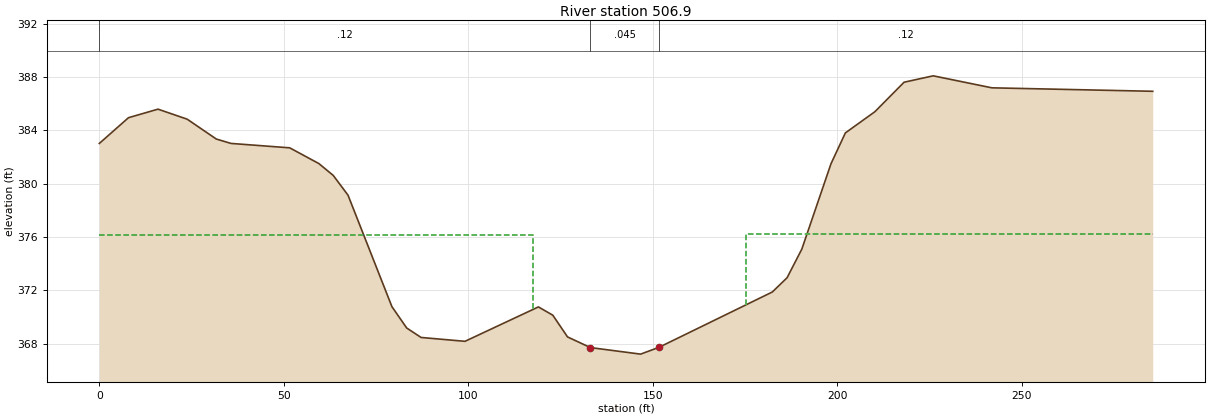
HEC-RAS study CHERRYRUN.prj: CHERRYRUN

--- CHERRYRUN.g01 (geometry) --- (continued)

Type RM Length L Ch R = 1 ,506.9   ,492.6,506.9,521
XS GIS Cut Line= 2
2384607.26031238411397.1651631742384473.24909747411145.031153008
#Sta/Elev= 30
       0  383.01     7.9  384.94    15.9  385.58    23.8  384.83    31.7  383.34
    35.7  383.01    51.6  382.68    59.5   381.5    63.4  380.61    67.4  379.13
    79.3  370.77    83.3  369.17    87.2  368.46    99.1  368.17     119  370.75
   122.9  370.13   126.9   368.5   133.1   367.7   146.7  367.21  151.68  367.72
   182.4  371.87   186.4  372.94   190.4  375.09   198.3  381.49   202.2   383.8
   210.2  385.39   218.1   387.6     226  388.08   241.9  387.18   285.5  386.92
#Mann= 3 ,-1 , 0
       0     .12       0   133.1    .045       0  151.68     .12       0
#XS Ineff= 2 , 0
          117.65  376.11  175.23          376.19
Permanent Ineff=
       F       F
Bank Sta=133.1,151.68
XS Rating Curve= 0 ,0
Exp/Cntr=0.3,0.1

Chan Stop Cuts=-1
Use User Specified Reach Order=0
Composite Channel Slope=5